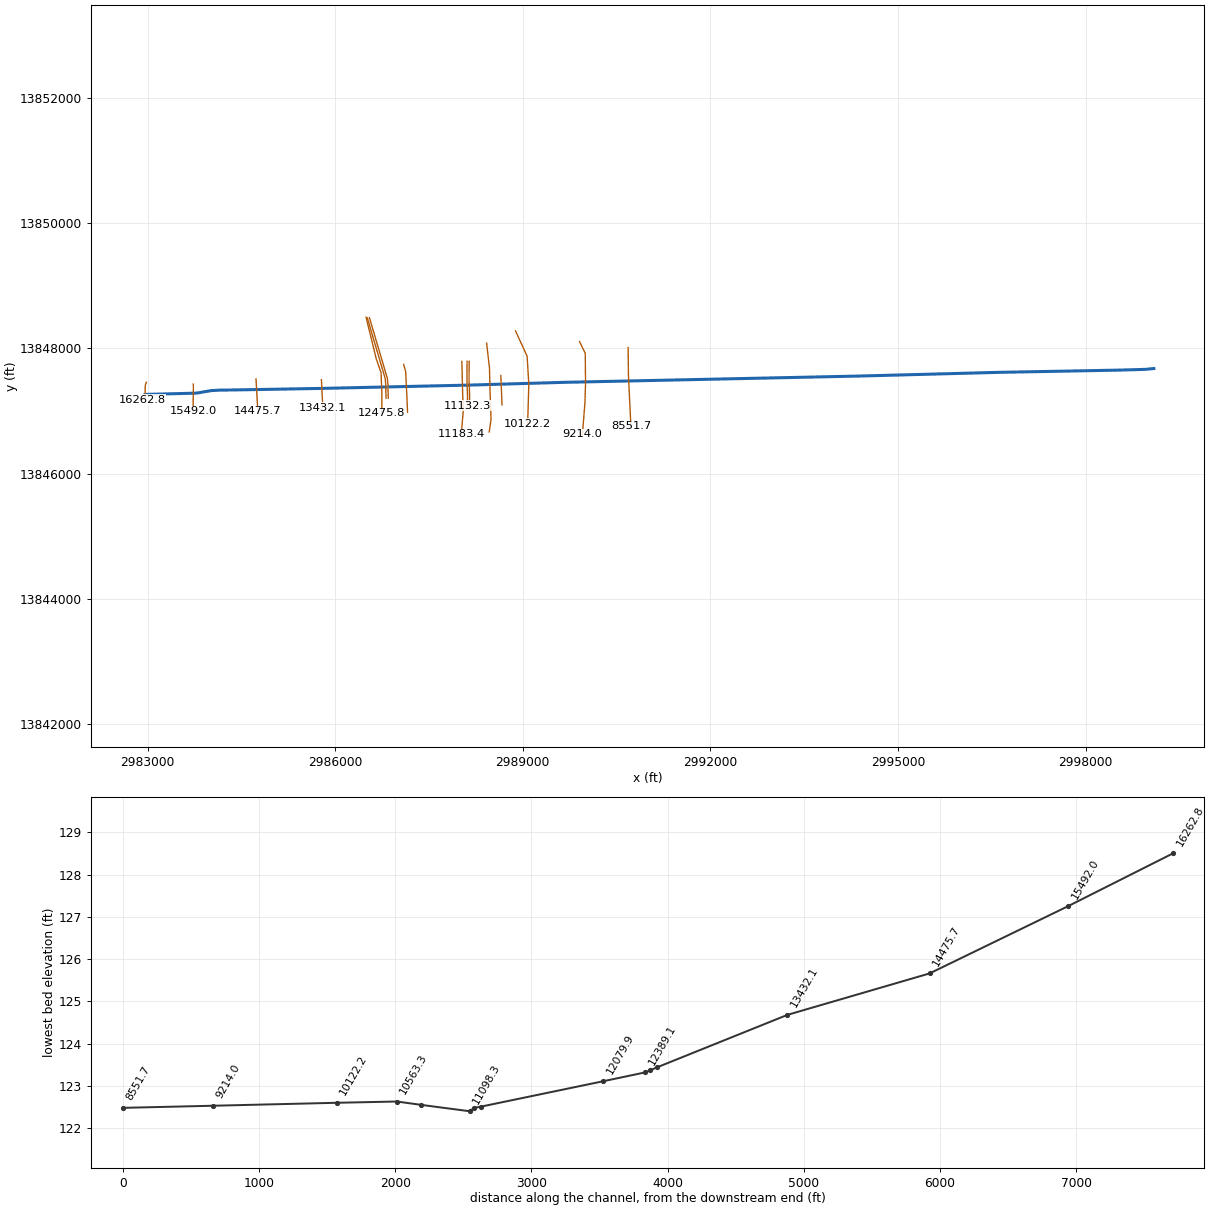
--- T101-03-00.PRJ (project) ---

Proj Title=T101-03-00
Current Plan=p02
Default Exp/Contr=.3,.1
English Units
Geom File=g01
Flow File=f01
Flow File=f02
Plan File=p01
Plan File=p02
Y Axis Title=Elevation
X Axis Title(PF)=Main Channel Distance
X Axis Title(XS)=Station
BEGIN DESCRIPTION:
HCFCD Unit T101-03-00
Flood Hazard Model
10, 2, 1, 0.2% Event
Filename T101-03-00.prj
Prepared by:  Watershed Concepts  Date:
Reviewed by:                      Date:
STATUS FINAL
END DESCRIPTION:
DSS File=dss
DSS Export Rating Curves= 0
DSS Export Rating Curve Sorted= 0
DSS Export Volume Flow Curves= 0
DXF OffsetX= 0
DXF OffsetY= 0
DXF ScaleX= 1
DXF ScaleY= 10

--- T101-03-00.p02 (plan) ---

Plan Title=Floodway
Version=Version 3.0.1  Mar 2001
Short Identifier=Floodway0607
Geom File=g01
Flow File=f02
Subcritical Flow
K Sum by GR= 0
Std Step Tol= 0.01
Critical Tol= 0.01
Num of Std Step Trials= 20
Max Error Tol= 0.3
Flow Tol Ratio= 0.001
Split Flow NTrial= 30
Split Flow Tol= 0.02
Split Flow Ratio= 0.02
Log Output Level= 0
Friction Slope Method= 1
Unsteady Friction Slope Method= 2
Parabolic Critical Depth
Global Vel Dist= 0 , 0 , 0
Global Log Level= 0
CheckData=True
Encroach Param=-1 ,0,0, 2
Encroach River=T101-03-00
Encroach Reach=Reach - 1
Encroach Node=16262.8
       1    4981  5012.5
Encroach Node=15492.0
       1  4987.4  5012.5
Encroach Node=14475.7
       1  4956.9    5043
Encroach Node=13432.1
       1  4957.1  5044.2
Encroach Node=12475.8
       1  4967.7  5044.5
Encroach Node=12424.1
       1  4967.7  5044.2
Encroach Node=12406.6
       1  4967.7  5044.2
Encroach Node=12389.1
       1  4967.7  5044.2
Encroach Node=12079.9
       1  4960.5  5050.6
Encroach Node=11183.4
       1  4922.1    5043
Encroach Node=11132.3
       1  4922.1    5043
Encroach Node=11115.3
       1  4922.1    5043
Encroach Node=11098.3
       1  4922.1    5043
Encroach Node=10744.5
       1  4955.5  5044.6
Encroach Node=10563.3
       1  4955.5  5044.6
Encroach Node=10122.2
       1  4954.2    5043
Encroach Node=9214.0
       1  4954.2  5049.4
Encroach Node=8551.7
       1  4954.2    5043
Encroach Node=8502.2
       1  4954.2    5043
Encroach Node=8452.7
       1  4954.2    5043
Encroach Node=7630.3
       1  4949.5    5048
Encroach Node=6505.4
       1  4945.4    5047
Encroach Node=5650.4
       1  4945.7    5053
Encroach Node=5145.7
       1  4947.4    5061
Encroach Node=5068.5
       1  4953.4  5057.4
Encroach Node=5051.5
       1  4953.4  5057.4
Encroach Node=5034.5
       1  4953.4  5057.4
Encroach Node=4627.8
       1  4938.2  5060.4
Encroach Node=4591.6
       1  4943.4  5060.4
Encroach Node=4549.6
       1  4943.4  5060.4
Encroach Node=4507.6
       1  4943.4  5060.4
Encroach Node=4006.1
       1  4939.5  5059.5
Encroach Node=3566.2
       1  4949.3  5053.9
Encroach Node=2596.8
       1  4946.2  5052.1
Encroach Node=1566.3
       1  4948.8  5057.1
Encroach Node=759.9
       1  4950.7  5040.8
Encroach Node=734.6
       1  4981.1    5029
Encroach Node=562.1
       1  4981.1    5029
Encroach Node=389.6
       1  4981.1    5029
Encroach Node=248.7
       1  4954.7    5035
Encroach Reach=T101-03-00_0002
Encroach Node=16262.8
       1    4981  5012.5
Encroach Node=15492.0
       1  4987.4  5012.5
Encroach Node=14475.7
       1  4956.9    5043
Encroach Node=13432.1
       1  4957.1  5044.2
Encroach Node=12475.8
       1  4967.7  5044.5
Encroach Node=12424.1
       1  4967.7  5044.2
Encroach Node=12406.6
       1  4967.7  5044.2
Encroach Node=12389.1
       1  4967.7  5044.2
Encroach Node=12079.9
       1  4960.5  5050.6
Encroach Node=11183.4
       1  4922.1    5043
Encroach Node=11132.3
       1  4922.1    5043
Encroach Node=11115.3
       1  4922.1    5043
Encroach Node=11098.3
       1  4922.1    5043
Encroach Node=10744.5
       1  4955.5  5044.6
Encroach Node=10563.3
       1  4955.5  5044.6
Encroach Node=10122.2
       1  4954.2    5043
Encroach Node=9214.0
       1  4954.2  5049.4
Encroach Node=8551.7
       1  4954.2    5043
Encroach Node=8502.2
       1  4954.2    5043
Encroach Node=8452.7
       1  4954.2    5043
Encroach Node=7630.3
       1  4949.5    5048
Encroach Node=6505.4
       1  4945.4    5047
Encroach Node=5650.4
       1  4945.7    5053
Encroach Node=5145.7
       1  4947.4    5061
Encroach Node=5068.5
       1  4953.4  5057.4
Encroach Node=5051.5
       1  4953.4  5057.4
Encroach Node=5034.5
       1  4953.4  5057.4
Encroach Node=4627.8
       1  4938.2  5060.4
Encroach Node=4591.6
       1  4943.4  5060.4
Encroach Node=4549.6
       1  4943.4  5060.4
Encroach Node=4507.6
       1  4943.4  5060.4
Encroach Node=4006.1
       1  4939.5  5059.5
Encroach Node=3566.2
       1  4949.3  5053.9
Encroach Node=2596.8
       1  4946.2  5052.1
Encroach Node=1566.3
       1  4948.8  5057.1
Encroach Node=759.9
       1  4950.7  5040.8
Encroach Node=734.6
       1  4981.1    5029
Encroach Node=562.1
       1  4981.1    5029
Encroach Node=389.6
       1  4981.1    5029
Encroach Node=248.7
       1  4954.7    5035
Computation Interval=1HOUR
Output Interval=1HOUR
Run HTab= 0
Run UNet= 0
Run PostProcess= 0
UNET Theta= 1
UNET ZTol= 0.02
UNET ZSATol= 0.1
UNET MxIter= 20
UNET MaxInSteps= 20
UNET DtIC= 0
UNET DtMin= 0
UNET MaxCRTS= 20
UNET WFStab= 2
UNET SFStab= 1
UNET WFX= 1
UNET SFX= 1
UNET Convert EG Bridges=-1
UNET Use Existing IB Tables=-1
Instantaneous Interval=1HOUR
Write IC File= 0
IC Time=0
Write Velocity= 0
Write Detailed= 0

--- T101-03-00.p01 (plan) ---

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Plan Title=FEMA Effective June 2007
Geom File=g01
Flow File=f01
DSS File=dss

--- T101-03-00.f02 (steady flow) ---

Flow Title=Floodway
Program Version=3.13
Number of Profiles= 2
Profile Names=1PCT_100yr,1PCTFloodway_100yrFW
River Rch & RM=T101-03-00,T101-03-00_0002       ,16262.8
     561     561
River Rch & RM=T101-03-00,T101-03-00_0002       ,14475.7
     657     657
River Rch & RM=T101-03-00,T101-03-00_0002       ,12424.1
     727     727
River Rch & RM=T101-03-00,T101-03-00_0002       ,10563.3
     792     792
River Rch & RM=T101-03-00,T101-03-00_0002       ,8551.7
     914     914
River Rch & RM=T101-03-00,T101-03-00_0002       ,5145.7
    1027    1027
River Rch & RM=T101-03-00,T101-03-00_0002       ,3566.2
    1136    1136
Boundary for River Rch & Prof#=T101-03-00,T101-03-00_0002       , 1
Up Type= 0
Dn Type= 3
Dn Slope=0.0009
Boundary for River Rch & Prof#=T101-03-00,T101-03-00_0002       , 2
Up Type= 0
Dn Type= 1
Dn Known WS=121.33
DSS Import GetInterval= 0
DSS Import GetPeak= 0
DSS Import FillOption= 0

--- T101-03-00.f01 (steady flow) ---

Flow Title=FEMA Effective June 2007
Program Version=3.13
Number of Profiles= 4
Profile Names=10PCT_10yr,2PCT_50yr,1PCT_100yr,0.2PCT_500yr
River Rch & RM=T101-03-00,T101-03-00_0002       ,16262.8
     297     470     561     831
River Rch & RM=T101-03-00,T101-03-00_0002       ,14475.7
     348     550     657     973
River Rch & RM=T101-03-00,T101-03-00_0002       ,12424.1
     384     608     727    1076
River Rch & RM=T101-03-00,T101-03-00_0002       ,10563.3
     419     663     792    1173
River Rch & RM=T101-03-00,T101-03-00_0002       ,8551.7
     483     765     914    1353
River Rch & RM=T101-03-00,T101-03-00_0002       ,5145.7
     543     860    1027    1520
River Rch & RM=T101-03-00,T101-03-00_0002       ,3566.2
     601     951    1136    1681
Boundary for River Rch & Prof#=T101-03-00,T101-03-00_0002       , 1
Up Type= 0
Dn Type= 3
Dn Slope=0.0009
Boundary for River Rch & Prof#=T101-03-00,T101-03-00_0002       , 2
Up Type= 0
Dn Type= 3
Dn Slope=0.0009
Boundary for River Rch & Prof#=T101-03-00,T101-03-00_0002       , 3
Up Type= 0
Dn Type= 3
Dn Slope=0.0009
Boundary for River Rch & Prof#=T101-03-00,T101-03-00_0002       , 4
Up Type= 0
Dn Type= 3
Dn Slope=0.0009
DSS Import GetInterval= 0
DSS Import GetPeak= 0
DSS Import FillOption= 0

--- T101-03-00.g01 (geometry) ---

Geom Title=T101-03-00 June 2007
Version=Version 3.0.1  Mar 2001

River Reach=T101-03-00      ,T101-03-00_0002
Reach XY= 17
      2982959.87     13847265.01      2983007.12     13847265.85
      2983784.25       13847285.      2984012.25       13847325.
      2984158.67     13847333.15      2984365.55     13847335.64
       2985783.8     13847360.57       2988121.8     13847412.91
      2989669.66     13847457.78      2990856.11      13847482.7
      2992134.78     13847510.12      2994355.63     13847557.48
      2995210.57     13847579.91      2996618.85      13847617.3
      2998510.69     13847652.19      2998951.87     13847664.66
       2999091.5       13847678.

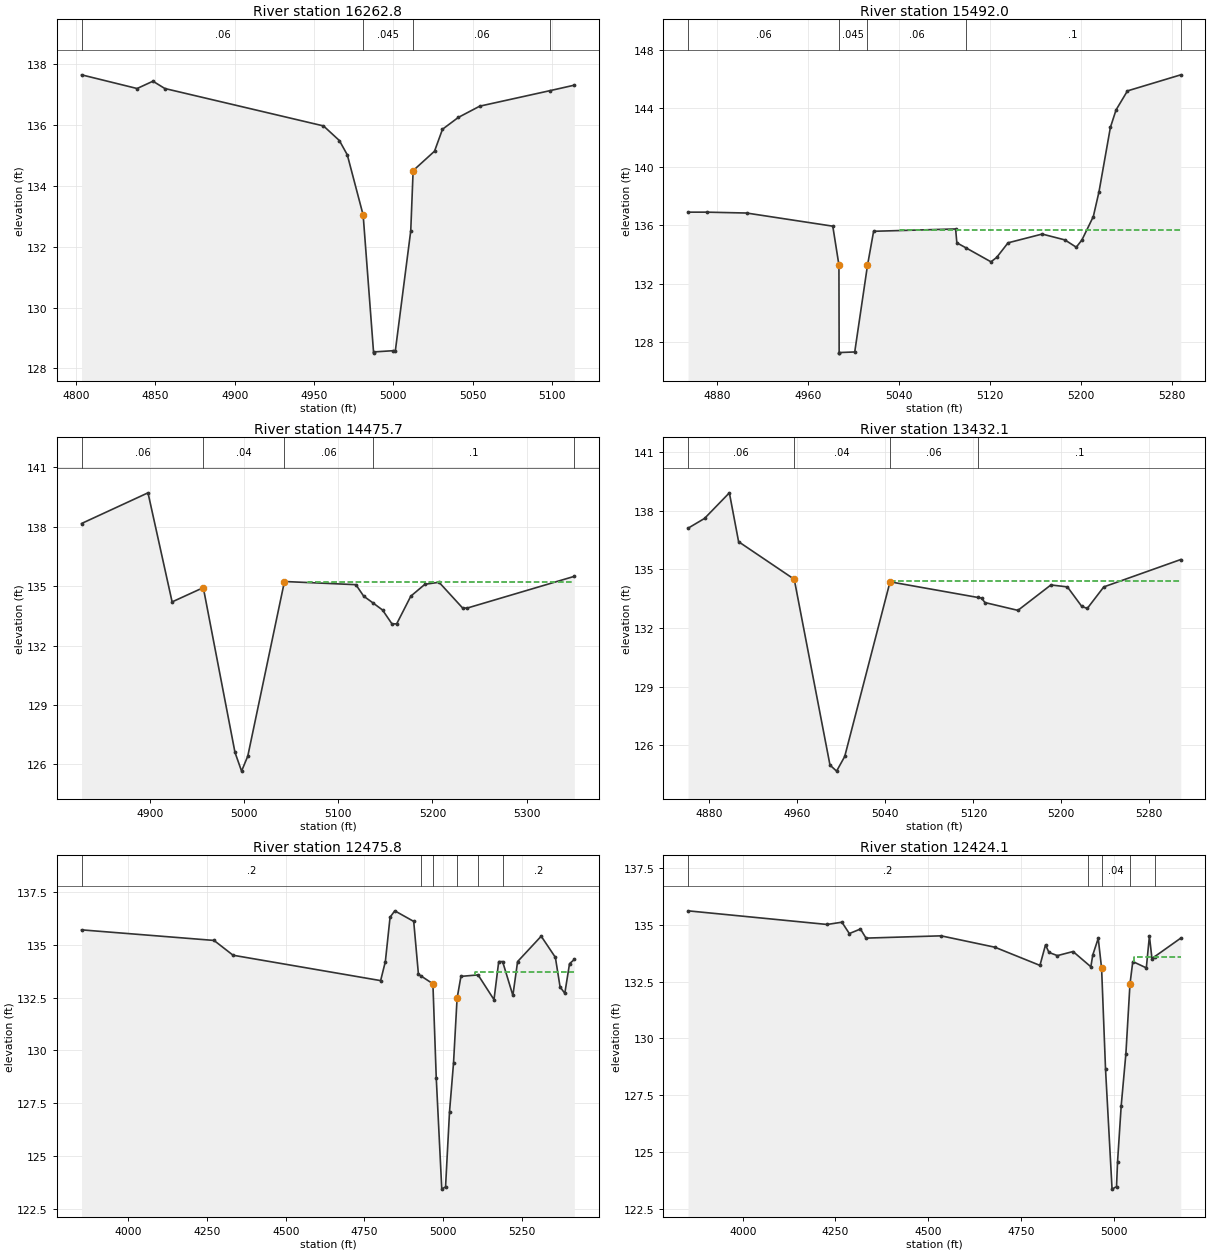
Type RM Length L Ch R = 1 ,16262.8 ,768.7,770.8,771.4
BEGIN DESCRIPTION:
Cross Section 16262.8 - Interpolated
END DESCRIPTION:
XS GIS Cut Line= 4
      2982979.78      13847458.5      2982962.21     13847409.03
      2982958.95     13847210.53      2982908.19      13847179.3
#Sta/Elev= 20
  4803.5  137.65  4838.5   137.2  4848.5  137.44    4856   137.2    4956  135.97
    4966  135.49    4971  135.02    4981  133.04  4987.6   128.5  4987.8  128.54
    5000  128.58  5001.3  128.58    5011  132.52  5012.5   134.5    5026  135.14
    5031  135.86    5041  136.25  5054.5  136.62  5098.8  137.13  5114.1  137.31
#Mann= 4 , 1 , 0
  4803.5     .06       0    4981    .045       0  5012.5     .06       0
  5098.8      .1       0
Bank Sta=4981,5012.5
XS Rating Curve= 0
Exp/Cntr=.3,.1

Type RM Length L Ch R = 1 ,15492.0 ,1012.3,1016.3,1025
BEGIN DESCRIPTION:
Cross Section 15492.0
END DESCRIPTION:
XS GIS Cut Line= 3
      2983729.47      13847428.8      2983731.84       13847412.
      2983727.04     13846995.12
#Sta/Elev= 26
  4854.7   136.9  4871.1   136.9  4906.2  136.84    4982  135.94  4987.4  133.28
  4987.6  127.25  4987.8  127.29  5001.3  127.33  5012.5  133.25  5017.9  135.59
    5090  135.75  5091.1   134.8  5098.8  134.47  5121.1   133.5  5126.1   133.8
  5136.1   134.8  5166.1   135.4  5186.1     135  5196.1   134.5  5201.1     135
  5211.1   136.6  5216.1   138.3  5226.1   142.7  5231.1   143.9  5241.1   145.2
    5288   146.3
#Mann= 5 , 1 , 0
  4854.7     .06       0  4987.4    .045       0  5012.5     .06       0
  5098.8      .1       0    5288      .2       0
#XS Ineff= 2 , 0
       0                    5041       0   135.7
Permanent Ineff=
       F       F
Bank Sta=4987.4,5012.5
XS Rating Curve= 0
Exp/Cntr=.3,.1

Type RM Length L Ch R = 1 ,14475.7 ,1044,1043.6,1043.5
BEGIN DESCRIPTION:
Cross Section 14475.7
END DESCRIPTION:
XS GIS Cut Line= 3
      2984733.08     13847514.29       2984733.3     13847512.63
      2984762.48     13846992.22
#Sta/Elev= 20
  4827.7  138.17  4898.2  139.72  4923.8  134.21  4956.9  134.93  4990.5  126.61
  4997.5  125.66  5004.1  126.42    5043  135.24  5118.8  135.08  5127.1   134.5
  5136.9  134.16  5147.1   133.8  5157.1   133.1  5162.1   133.1  5177.1   134.5
  5192.1   135.1  5207.1   135.2  5232.1   133.9  5237.1   133.9  5350.6   135.5
#Mann= 5 , 1 , 0
  4827.7     .06       0  4956.9     .04       0    5043     .06       0
  5136.9      .1       0  5350.6      .2       0
#XS Ineff= 2 , 0
       0  4956.9  134.93    5068       0   135.2
Permanent Ineff=
       F       F
Bank Sta=4956.9,5043
XS Rating Curve= 0
Exp/Cntr=.3,.1

Type RM Length L Ch R = 1 ,13432.1 ,956.9,956.3,954.7
BEGIN DESCRIPTION:
Cross Section 13432.1
END DESCRIPTION:
XS GIS Cut Line= 3
      2985779.27     13847499.95      2985797.07     13847148.46
      2985792.49     13847052.41
#Sta/Elev= 19
  4860.5   137.1  4875.5   137.6  4898.1  138.91  4906.5  136.41  4957.1  134.49
  4989.6  124.99  4995.6  124.68    5003  125.43  5044.2  134.36  5124.1  133.56
  5127.4  133.53  5130.5   133.3  5160.5   132.9  5190.5   134.2  5205.5   134.1
  5218.6   133.1  5223.6     133  5238.6   134.1  5308.6   135.5
#Mann= 4 , 1 , 0
  4860.5     .06       0  4957.1     .04       0  5044.2     .06       0
  5124.1      .1       0
#XS Ineff= 2 , 0
       0                    5045       0   134.4
Permanent Ineff=
       F       F
Bank Sta=4957.1,5044.2
XS Rating Curve= 0
Exp/Cntr=.3,.1

Type RM Length L Ch R = 1 ,12475.8 ,6.9,51.7,6.9
BEGIN DESCRIPTION:
Cross Section 12475.8-Interpolated
END DESCRIPTION:
XS GIS Cut Line= 6
      2986493.07     13848497.99      2986655.71     13847835.24
      2986732.96     13847611.61      2986745.16     13847314.79
      2986745.16     13847070.84      2986745.16     13846965.12
#Sta/Elev= 30
  3851.3   135.7  4272.2   135.2  4332.8   134.5  4801.6   133.3  4816.6   134.2
  4831.6   136.3  4846.6   136.6  4906.7   136.1  4921.7   133.6  4930.9  133.51
  4967.7  133.15  4978.3  128.71  4995.9  123.44  5007.9  123.55  5020.5   127.1
  5033.2   129.4  5044.5  132.46  5056.8   133.5  5111.2  133.57  5161.8   132.4
  5176.8   134.2  5189.2   134.2  5221.8   132.6  5236.8   134.2  5311.8   135.4
  5356.8   134.4  5371.8     133  5386.8   132.7  5401.8   134.1    5417   134.3
#Mann= 6 , 1 , 0
  3851.3      .2       0  4930.9     .06       0  4967.7     .04       0
  5044.5     .06       0  5111.2      .1       0  5189.2      .2       0
#XS Ineff= 2 , 0
       0                    5103       0   133.7
Permanent Ineff=
       F       F
Bank Sta=4967.7,5044.5
XS Rating Curve= 0
Exp/Cntr=.5,.3

Type RM Length L Ch R = 1 ,12424.1 ,35,35,35
BEGIN DESCRIPTION:
Upstream Section of Bridge/Culvert/Weir
END DESCRIPTION:
XS GIS Cut Line= 6
      2986512.41     13848489.22      2986798.67     13847520.59
      2986808.53     13847419.06      2986808.53     13847341.81
      2986813.63     13847221.13      2986813.29     13847202.42
#Sta/Elev= 30
  3852.4  135.61  4227.4  135.01  4267.4  135.11  4287.4  134.61  4317.4  134.81
  4332.4  134.41  4534.8  134.51  4679.8  134.01  4801.4  133.21  4816.4  134.11
  4825.8  133.78  4848.5  133.64  4890.7  133.82  4938.7  133.15  4943.9  133.67
  4958.6   134.4  4967.7  133.08  4978.3  128.64  4995.9  123.37  5007.9  123.48
  5010.7  124.57  5020.5  127.03  5033.2  129.33  5044.2  132.39  5051.8  133.38
  5088.3   133.1  5096.6   134.5  5103.5  133.51  5111.2   133.6  5181.2  134.41
#Mann= 5 , 1 , 0
  3852.4      .2       0  4930.9     .06       0  4967.7     .04       0
  5044.2     .06       0  5111.2      .1       0
#XS Ineff= 2 , 0
       0  4961.3   133.6    5054       0   133.6
Permanent Ineff=
       F       F
Bank Sta=4967.7,5044.2
XS Rating Curve= 0
Exp/Cntr=.5,.3

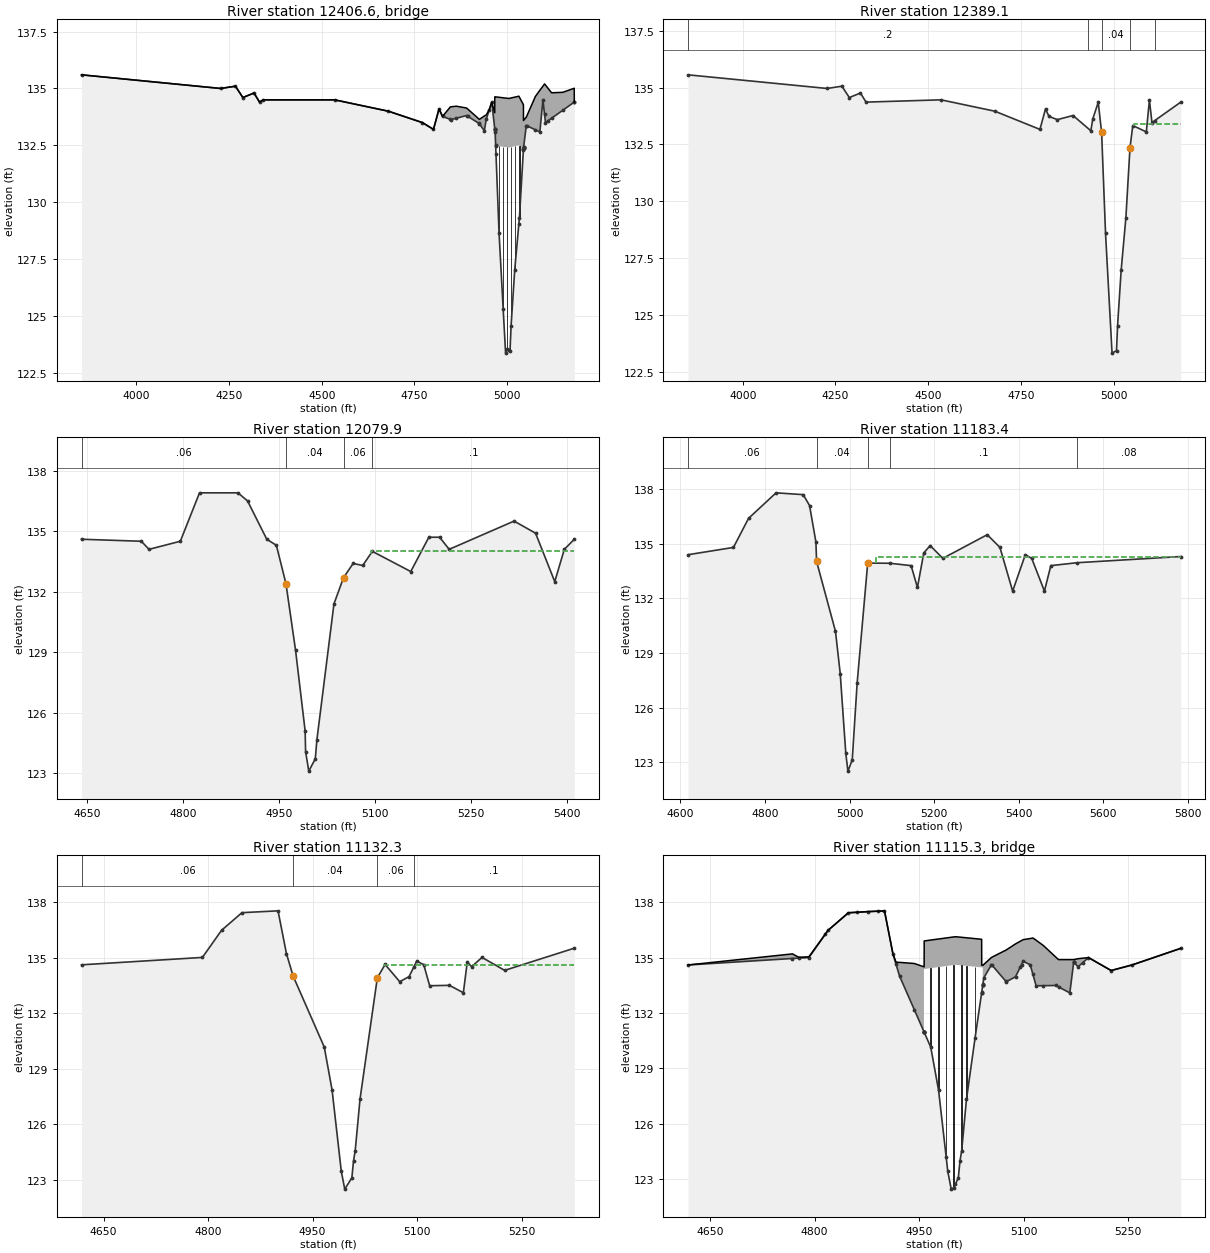
Type RM Length L Ch R = 3 ,12406.6 ,,,
BEGIN DESCRIPTION:
INTERSTATE 10-FRONTAGE ROAD
Structure ID: T13-9
END DESCRIPTION:
Bridge Culvert--1,0,-1,-1, 0
Deck Dist Width WeirC Skew NumUp NumDn MinLoCord MaxHiCord MaxSubmerge Is_Ogee
10,15,2.6,0, 40, 40, , , .95, 0, 1,1,,
  3852.4  4227.4  4267.4  4287.4  4317.4  4332.4  4342.4  4534.8  4679.8  4771.4
  4801.4  4816.4  4825.8    4847    4863  4890.7  4925.2  4938.7  4943.9  4951.9
  4958.6 4966.59  4966.7  4967.7  4969.1  5004.8  5031.7 5043.89    5044 5044.11
  5051.8  5076.3  5088.3  5096.6  5100.9  5103.5  5119.9  5150.1    5181  5181.2
   135.6     135   135.1   134.6   134.8   134.4   134.5   134.5     134   133.5
   133.2   134.1  133.77  134.19  134.22  134.14  133.64  133.79  133.84  134.07
   134.4  133.93  134.63  134.63  134.63  134.56  134.66  134.29  134.29  133.59
  133.74  134.65  134.92   135.1   135.2  135.15  134.81  134.83  135.01   134.4
   135.6     135   135.1   134.6   134.8   134.4   134.5   134.5     134   133.5
   133.2   134.1  133.77  133.64  133.69  133.81  133.44  133.14  133.66  134.06
  134.39  133.23  133.22  133.07  132.48   132.4   132.5  132.29  132.32  132.35
  133.37  133.18  133.09  134.49  133.87   133.5  133.69  134.04   134.4   134.4
  3852.4  4227.4  4267.4  4287.4  4317.4  4332.4  4342.4  4534.8  4679.8  4771.4
  4801.4  4816.4  4825.8    4847    4863  4890.7  4925.2  4938.7  4943.9  4951.9
  4958.6 4966.59  4966.7  4967.7  4969.1  5004.8  5031.7 5043.89    5044 5044.11
  5051.8  5076.3  5088.3  5096.6  5100.9  5103.5  5119.9  5150.1    5181  5181.2
   135.6     135   135.1   134.6   134.8   134.4   134.5   134.5     134   133.5
   133.2   134.1  133.77  134.19  134.22  134.14  133.64  133.79  133.84  134.07
   134.4  133.93  134.63  134.63  134.63  134.56  134.66  134.29  134.29  133.59
  133.74  134.65  134.92   135.1   135.2  135.15  134.81  134.83  135.01   134.4
  135.57  134.97  135.07  134.57  134.77  134.37  134.47  134.47  133.97  133.47
  133.17  134.07  133.74  133.61  133.66  133.78  133.41  133.11  133.63  134.03
  134.36   133.2  133.19  133.04  132.45  132.37  132.47  132.26  132.29  132.32
  133.34  133.15  133.06  134.46  133.84  133.47  133.66  134.01  134.37  134.37
Pier Skew, UpSta & Num, DnSta & Num=  ,4978.3, 2 ,4978.3, 2 , 0 , 0 , 0 ,,
       1       1
  127.48  133.45
       1       1
  127.45  133.42
Pier Skew, UpSta & Num, DnSta & Num=  ,4989.2, 2 ,4989.2, 2 , 0 , 0 , 0 ,,
       1       1
   124.2  133.43
       1       1
  124.17   133.4
Pier Skew, UpSta & Num, DnSta & Num=  ,5000, 2 ,5000, 2 , 0 , 0 , 0 ,,
       1       1
  122.51  133.41
       1       1
  122.48  133.38
Pier Skew, UpSta & Num, DnSta & Num=  ,5010.7, 2 ,5010.7, 2 , 0 , 0 , 0 ,,
       1       1
  123.37  133.42
       1       1
  123.34  133.39
Pier Skew, UpSta & Num, DnSta & Num=  ,5020.5, 2 ,5020.5, 2 , 0 , 0 , 0 ,,
       1       1
  125.89  133.46
       1       1
  125.86  133.43
Pier Skew, UpSta & Num, DnSta & Num=  ,5033.2, 2 ,5033.2, 2 , 0 , 0 , 0 ,,
       1       1
  128.23  133.47
       1       1
   128.2  133.44
Abutment Skew #Up #Dn= , 2 , 2
  4968.9    4970
  132.48  132.11
  4968.9    4970
  132.45  132.08
BR Coef= 1 , 1 , 0 ,1.25, 0 ,,,.8,0,2,0,
WSPro=,,,, 1 ,,,, 0 ,,,, 0 ,,,,-1 ,-1 ,-1 , 0 , 0 , 0 , 0 , 0
BR U #Sta/Elev= 62
  3852.4   135.6  4227.4     135  4267.4   135.1  4287.4   134.6  4317.4   134.8
  4332.4   134.4  4342.4   134.5  4534.8   134.5  4679.8     134  4771.4   133.5
  4801.4   133.2  4816.4   134.1  4825.8  133.77    4847  133.64  4848.5  133.63
    4863  133.69  4890.7  133.81  4894.3  133.77  4924.4  133.46  4925.2  133.44
  4938.7  133.14  4943.9  133.66  4951.9  134.06  4958.6  134.39 4966.59  133.23
  4966.7  133.22 4966.81   133.2  4966.9  133.19  4967.7  133.07 4969.01  132.52
  4969.1  132.48    4970  132.11  4978.3  128.63  4989.3  125.32  4995.9  123.36
    5000  123.53  5004.8  123.49  5007.9  123.47  5010.7  124.56  5020.5  127.02
  5031.7  129.05  5033.2  129.32 5043.89  132.29    5044  132.32 5044.11  132.35
  5044.2  132.38  5044.3  132.39 5044.39   132.4  5044.5  132.42  5044.6  132.43
  5051.8  133.37  5053.2  133.36  5076.3  133.18  5088.3  133.09  5096.6  134.49
  5100.9  133.87  5103.5   133.5  5111.2  133.59  5119.9  133.69  5150.1  134.04
    5181   134.4  5181.2   134.4
BR U #Mann= 5
  3852.4      .2  4930.9     .06  4967.7     .04  5044.2     .06  5111.2      .1
BR U Banks=4967.7,5044.2
BR D #Sta/Elev= 62
  3852.4  135.57  4227.4  134.97  4267.4  135.07  4287.4  134.57  4317.4  134.77
  4332.4  134.37  4342.4  134.47  4534.8  134.47  4679.8  133.97  4771.4  133.47
  4801.4  133.17  4816.4  134.07  4825.8  133.74    4847  133.61  4848.5   133.6
    4863  133.66  4890.7  133.78  4894.3  133.74  4924.4  133.43  4925.2  133.41
  4938.7  133.11  4943.9  133.63  4951.9  134.03  4958.6  134.36 4966.59   133.2
  4966.7  133.19 4966.81  133.17  4966.9  133.16  4967.7  133.04 4969.01  132.49
  4969.1  132.45    4970  132.08  4978.3   128.6  4989.3  125.29  4995.9  123.33
    5000   123.5  5004.8  123.46  5007.9  123.44  5010.7  124.53  5020.5  126.99
  5031.7  129.02  5033.2  129.29 5043.89  132.26    5044  132.29 5044.11  132.32
  5044.2  132.35  5044.3  132.36 5044.39  132.37  5044.5  132.39  5044.6   132.4
  5051.8  133.34  5053.2  133.33  5076.3  133.15  5088.3  133.06  5096.6  134.46
  5100.9  133.84  5103.5  133.47  5111.2  133.56  5119.9  133.66  5150.1  134.01
    5181  134.37  5181.2  134.37
BR D #Mann= 5
  3852.4      .2  4930.9     .06  4967.7     .04  5044.2     .06  5111.2      .1
BR D Banks=4967.7,5044.2
BC Design=,, 0 ,, 0 ,,,,,,
BC HTab HWMax=135.61

Type RM Length L Ch R = 1 ,12389.1 ,309.2,309.2,309.2
BEGIN DESCRIPTION:
Downstream Section of Bridge/Culvert/Weir
END DESCRIPTION:
XS GIS Cut Line= 6
       2986547.4       13848490.      2986833.67     13847521.37
      2986843.53     13847419.84      2986843.53     13847342.59
      2986848.63     13847221.91      2986848.28      13847203.2
#Sta/Elev= 30
  3852.4  135.56  4227.4  134.96  4267.4  135.06  4287.4  134.56  4317.4  134.76
  4332.4  134.36  4534.8  134.46  4679.8  133.96  4801.4  133.16  4816.4  134.06
  4825.8  133.73  4848.5  133.59  4890.7  133.77  4938.7   133.1  4943.9  133.62
  4958.6  134.35  4967.7  133.03  4978.3  128.59  4995.9  123.32  5007.9  123.43
  5010.7  124.52  5020.5  126.98  5033.2  129.28  5044.2  132.34  5051.8  133.33
  5088.3  133.05  5096.6  134.45  5103.5  133.46  5111.2  133.55  5181.2  134.36
#Mann= 5 , 1 , 0
  3852.4      .2       0  4930.9     .06       0  4967.7     .04       0
  5044.2     .06       0  5111.2      .1       0
#XS Ineff= 2 , 0
       0  4961.3   133.4    5054       0   133.4
Permanent Ineff=
       F       F
Bank Sta=4967.7,5044.2
XS Rating Curve= 0
Exp/Cntr=.5,.3

Type RM Length L Ch R = 1 ,12079.9 ,895.4,896.5,897.1
BEGIN DESCRIPTION:
Cross Section 12079.9-Interpolated
END DESCRIPTION:
XS GIS Cut Line= 6
      2987094.45     13847745.36      2987126.86     13847629.87
      2987132.29     13847519.76      2987138.23     13847389.03
      2987147.15     13847220.66      2987156.89     13846979.88
#Sta/Elev= 30
  4640.8   134.6  4734.3   134.5  4746.3   134.1  4795.3   134.5  4825.3   136.9
  4885.4   136.9  4900.4   136.5  4930.5   134.6  4945.5   134.3  4960.5   132.4
  4975.5   129.1  4990.5   125.1  4991.2  124.08  4996.2  123.11  5006.4  123.72
  5008.8  124.64  5035.6   131.4  5050.6   132.7  5065.6   133.4  5080.6   133.3
  5095.6     134  5155.7     133    5184   134.7  5200.8   134.7  5215.8   134.1
  5317.3   135.5  5350.9   134.9  5380.9   132.5  5395.9   134.1  5411.5   134.6
#Mann= 4 , 1 , 0
  4640.8     .06       0  4960.5     .04       0  5050.6     .06       0
  5095.6      .1       0
#XS Ineff= 2 , 0
       0                  5093.2       0     134
Permanent Ineff=
       F       F
Bank Sta=4960.5,5050.6
XS Rating Curve= 0
Exp/Cntr=.3,.1

Type RM Length L Ch R = 1 ,11183.4 ,52.2,51.1,50.7
BEGIN DESCRIPTION:
Cross Section 11183.4-Interpolated
END DESCRIPTION:
XS GIS Cut Line= 4
      2988025.26     13847792.73      2988034.47     13847408.97
      2988046.75     13846991.44      2988016.05     13846629.17
#Sta/Elev= 30
  4618.1   134.4  4725.5   134.8  4761.3   136.4  4826.3   137.8  4890.5   137.7
  4905.5   137.1  4920.5   135.1  4922.1  134.03  4966.8  130.19    4978  127.87
  4991.2  123.48  4996.2  122.51  5006.4  123.12  5018.1  127.37    5043  133.94
  5095.6  133.93  5145.6   133.8  5160.6   132.6  5175.6   134.5  5190.7   134.9
  5220.7   134.2  5325.7   135.5  5355.7   134.8  5385.7   132.4  5415.7   134.4
  5430.8   134.2  5460.9   132.4    5476   133.8    5538  133.96  5783.3   134.3
#Mann= 5 , 1 , 0
  4618.1     .06       0  4922.1     .04       0    5043     .06       0
  5095.6      .1       0    5538     .08       0
#XS Ineff= 2 , 0
       0                  5062.5       0   134.3
Permanent Ineff=
       F       F
Bank Sta=4922.1,5043
XS Rating Curve= 0
Exp/Cntr=.5,.3

Type RM Length L Ch R = 1 ,11132.3 ,34,34,34
BEGIN DESCRIPTION:
Upstream Section of Bridge/Culvert/Weir
END DESCRIPTION:
XS GIS Cut Line= 6
      2988109.19     13847794.29      2988106.62     13847594.13
      2988106.62     13847486.18      2988111.52     13847358.61
      2988115.91     13847233.49       2988112.7     13847087.02
#Sta/Elev= 30
  4618.3  134.61  4791.8  135.01  4819.4  136.48  4848.6  137.43  4900.4  137.53
  4912.5  135.21  4922.1     134  4966.8  130.16    4978  127.84  4991.2  123.45
  4996.2  122.48  5006.4  123.09  5008.8  124.01  5011.2  124.55  5018.1  127.34
    5043  133.91  5054.1  134.63  5075.1   133.7  5088.5  133.97  5095.6  134.51
  5099.5  134.81  5109.6  134.62  5118.1  133.48  5146.5   133.5  5166.5   133.1
  5172.1  134.77  5178.3  134.51  5193.3  135.01  5225.8  134.31  5325.8  135.51
#Mann= 4 , 1 , 0
  4618.3     .06       0  4922.1     .04       0    5043     .06       0
  5095.6      .1       0
#XS Ineff= 2 , 0
       0  4916.5   134.5    5053       0   134.6
Permanent Ineff=
       F       F
Bank Sta=4922.1,5043
XS Rating Curve= 0
Exp/Cntr=.5,.3

Type RM Length L Ch R = 3 ,11115.3 ,,,
BEGIN DESCRIPTION:
INTERSTATE 10-FRONTAGE ROAD
Structure ID: T13-8
END DESCRIPTION:
Bridge Culvert--1,0,-1,-1, 0
Deck Dist Width WeirC Skew NumUp NumDn MinLoCord MaxHiCord MaxSubmerge Is_Ogee
10,14,2.6,0, 39, 39, , , .95, 0, 1,1,,
  4618.3  4768.3  4777.1  4791.8  4819.4  4848.6  4900.4  4912.5    4917  4922.1
  4943.2 4957.01  4957.1 4957.29  4957.4  5002.3  5039.9 5040.01 5041.49  5041.6
  5041.7    5043  5054.1  5075.1  5088.5  5099.5  5109.6  5113.5  5118.1  5128.6
  5146.5  5150.3  5166.5  5172.1  5178.3  5193.3  5225.8  5255.8  5325.8
   134.6   135.2  135.02  135.04  136.48  137.43  137.53  135.21  134.75  134.74
  134.68   134.5   134.5   134.5   135.9  136.13  135.99  134.59  134.58  134.58
  134.58  134.63  135.01  135.41  135.74  135.97  136.03  136.06  135.94  135.65
  135.02  134.89  134.89  134.89  134.94     135   134.3   134.6   135.5
   134.6  134.95  134.97     135  136.47  137.42  137.52   135.2  134.63  133.99
  132.18  130.99  134.38  134.38  134.38  134.61  134.47  134.47  134.46  133.54
  133.56   133.9  134.62  133.69  133.96   134.8  134.61  134.09  133.47  133.48
  133.49  133.41  133.09  134.76   134.5     135   134.3   134.6   135.5
  4618.3  4768.3  4777.1  4791.8  4819.4  4848.6  4900.4  4912.5    4917  4922.1
  4943.2 4957.01  4957.1 4957.29  4957.4  5002.3  5039.9 5040.01 5041.49  5041.6
  5041.7    5043  5054.1  5075.1  5088.5  5099.5  5109.6  5113.5  5118.1  5128.6
  5146.5  5150.3  5166.5  5172.1  5178.3  5193.3  5225.8  5255.8  5325.8
   134.6   135.2  135.02  135.04  136.48  137.43  137.53  135.21  134.75  134.74
  134.68   134.5   134.5   134.5   135.9  136.13  135.99  134.59  134.58  134.58
  134.58  134.63  135.01  135.41  135.74  135.97  136.03  136.06  135.94  135.65
  135.02  134.89  134.89  134.89  134.94     135   134.3   134.6   135.5
  134.53  134.88   134.9  134.93   136.4  137.35  137.45  135.13  134.56  133.92
  132.11  130.92  134.31  134.31  134.31  134.54   134.4   134.4  134.39  133.47
  133.49  133.83  134.55  133.62  133.89  134.73  134.54  134.02   133.4  133.41
  133.42  133.34  133.02  134.69  134.43  134.93  134.23  134.53  135.43
Pier Skew, UpSta & Num, DnSta & Num=  ,4966.8, 2 ,4966.8, 2 , 0 , 0 , 0 ,,
       1       1
  129.05  135.43
       1       1
  128.98  135.36
Pier Skew, UpSta & Num, DnSta & Num=  ,4978, 2 ,4978, 2 , 0 , 0 , 0 ,,
       1       1
  126.66  135.49
       1       1
  126.59  135.42
Pier Skew, UpSta & Num, DnSta & Num=  ,4988.9, 2 ,4988.9, 2 , 0 , 0 , 0 ,,
       1       1
  123.06  135.54
       1       1
  122.99  135.47
Pier Skew, UpSta & Num, DnSta & Num=  ,4999.8, 2 ,4999.8, 2 , 0 , 0 , 0 ,,
       1       1
  121.53   135.6
       1       1
  121.46  135.53
Pier Skew, UpSta & Num, DnSta & Num=  ,5011.2, 2 ,5011.2, 2 , 0 , 0 , 0 ,,
       1       1
  123.43  135.58
       1       1
  123.36  135.51
Pier Skew, UpSta & Num, DnSta & Num=  ,5018.1, 2 ,5018.1, 2 , 0 , 0 , 0 ,,
       1       1
  126.13  135.55
       1       1
  126.06  135.48
Pier Skew, UpSta & Num, DnSta & Num=  ,5030.4, 2 ,5030.4, 2 , 0 , 0 , 0 ,,
       1       1
  129.51  135.51
       1       1
  129.44  135.44
BR Coef= 1 , 1 , 0 ,1.25, 0 ,,,.8,0,2,0,
WSPro=,,,, 1 ,,,, 0 ,,,, 0 ,,,,-1 ,-1 ,-1 , 0 , 0 , 0 , 0 , 0
BR U #Sta/Elev= 65
  4618.3   134.6  4768.3  134.95  4777.1  134.97  4791.8     135  4815.6  136.27
  4819.4  136.47  4848.6  137.42  4861.3  137.45  4876.7  137.49  4890.5  137.51
  4900.4  137.52  4912.5   135.2    4917  134.63  4922.1  133.99  4943.2  132.18
 4957.01  130.99  4957.1  130.98  4957.2  130.97 4957.29  130.97  4957.4  130.96
 4957.51  130.95  4966.8  130.15    4978  127.83  4988.9  124.23  4991.2  123.44
  4996.2  122.47  4999.8  122.54  5002.3  122.74  5006.4  123.08  5008.8     124
  5011.2  124.54  5018.1  127.33  5030.4  130.64 5039.79  133.07  5039.9   133.1
 5040.01  133.13  5041.4  133.49 5041.49  133.51  5041.6  133.54  5041.7  133.56
    5043   133.9  5053.8   134.6  5054.1  134.62  5074.3  133.73  5075.1  133.69
  5088.5  133.96  5095.6   134.5  5097.2  134.62  5099.5   134.8  5109.6  134.61
  5113.5  134.09  5118.1  133.47  5128.6  133.48  5146.5  133.49  5150.3  133.41
  5166.5  133.09  5172.1  134.76  5172.2  134.76  5172.3  134.76  5178.3   134.5
  5185.2  134.73  5193.3     135  5225.8   134.3  5255.8   134.6  5325.8   135.5
BR U #Mann= 4
  4618.3     .06  4922.1     .04    5043     .06  5095.6      .1
BR U Banks=4922.1,5043
BR D #Sta/Elev= 65
  4618.3  134.53  4768.3  134.88  4777.1   134.9  4791.8  134.93  4815.6   136.2
  4819.4   136.4  4848.6  137.35  4861.3  137.38  4876.7  137.42  4890.5  137.44
  4900.4  137.45  4912.5  135.13    4917  134.56  4922.1  133.92  4943.2  132.11
 4957.01  130.92  4957.1  130.91  4957.2   130.9 4957.29   130.9  4957.4  130.89
 4957.51  130.88  4966.8  130.08    4978  127.76  4988.9  124.16  4991.2  123.37
  4996.2   122.4  4999.8  122.47  5002.3  122.67  5006.4  123.01  5008.8  123.93
  5011.2  124.47  5018.1  127.26  5030.4  130.57 5039.79     133  5039.9  133.03
 5040.01  133.06  5041.4  133.42 5041.49  133.44  5041.6  133.47  5041.7  133.49
    5043  133.83  5053.8  134.53  5054.1  134.55  5074.3  133.66  5075.1  133.62
  5088.5  133.89  5095.6  134.43  5097.2  134.55  5099.5  134.73  5109.6  134.54
  5113.5  134.02  5118.1   133.4  5128.6  133.41  5146.5  133.42  5150.3  133.34
  5166.5  133.02  5172.1  134.69  5172.2  134.69  5172.3  134.69  5178.3  134.43
  5185.2  134.66  5193.3  134.93  5225.8  134.23  5255.8  134.53  5325.8  135.43
BR D #Mann= 4
  4618.3     .06  4922.1     .04    5043     .06  5095.6      .1
BR D Banks=4922.1,5043
BC Design=,, 0 ,, 0 ,,,,,,
BC HTab HWMax=137.53

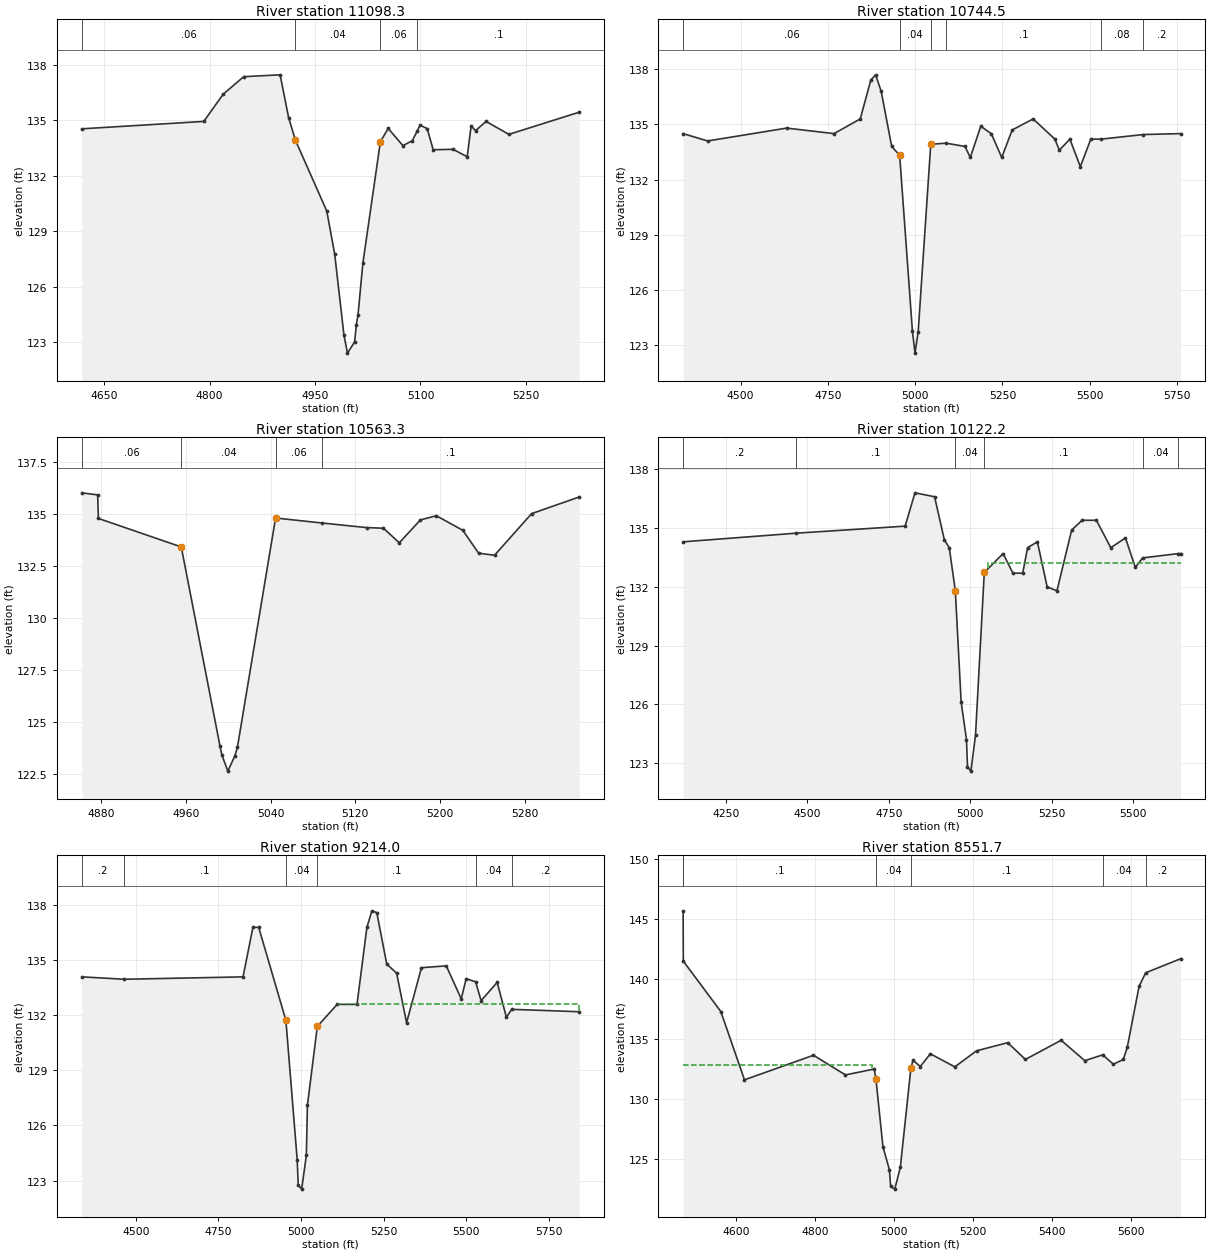
Type RM Length L Ch R = 1 ,11098.3 ,353.8,353.8,353.8
BEGIN DESCRIPTION:
Downstream Section of Bridge/Culvert/Weir
END DESCRIPTION:
XS GIS Cut Line= 6
      2988143.18     13847795.05      2988140.62     13847594.89
      2988140.62     13847486.94      2988145.52     13847359.37
      2988149.91     13847234.25      2988146.69     13847087.78
#Sta/Elev= 30
  4618.3  134.53  4791.8  134.93  4819.4   136.4  4848.6  137.35  4900.4  137.45
  4912.5  135.13  4922.1  133.92  4966.8  130.08    4978  127.76  4991.2  123.37
  4996.2   122.4  5006.4  123.01  5008.8  123.93  5011.2  124.47  5018.1  127.26
    5043  133.83  5054.1  134.55  5075.1  133.62  5088.5  133.89  5095.6  134.43
  5099.5  134.73  5109.6  134.54  5118.1   133.4  5146.5  133.42  5166.5  133.02
  5172.1  134.69  5178.3  134.43  5193.3  134.93  5225.8  134.23  5325.8  135.43
#Mann= 4 , 1 , 0
  4618.3     .06       0  4922.1     .04       0    5043     .06       0
  5095.6      .1       0
#XS Ineff= 2 , 0
       0  4916.5   134.3    5053       0   134.4
Permanent Ineff=
       F       F
Bank Sta=4922.1,5043
XS Rating Curve= 0
Exp/Cntr=.5,.3

Type RM Length L Ch R = 1 ,10744.5 ,180.8,181.2,181.7
BEGIN DESCRIPTION:
Cross Section 10744.5-Interpolated
END DESCRIPTION:
XS GIS Cut Line= 5
      2988421.33     13848085.04      2988467.35     13847682.21
      2988473.49     13847408.97      2988491.91     13846865.57
      2988463.68     13846665.39
#Sta/Elev= 30
  4335.4   134.5  4405.5   134.1    4632   134.8  4767.7   134.5  4842.7   135.3
  4872.7   137.4  4886.6   137.7  4902.7   136.8  4932.7   133.8  4955.5  133.32
  4992.1  123.75  4999.5  122.55  5008.6  123.71  5044.6  133.92  5088.6  133.98
  5142.8   133.8  5157.8   133.2  5187.9   134.9  5217.9   134.5  5247.9   133.2
  5277.9   134.7  5337.9   135.3    5400   134.2    5413   133.6    5443   134.2
    5473   132.7    5503   134.2  5532.7   134.2  5653.7  134.45    5760   134.5
#Mann= 6 , 1 , 0
  4335.4     .06       0  4955.5     .04       0  5044.6     .06       0
  5088.6      .1       0  5532.7     .08       0  5653.7      .2       0
Bank Sta=4955.5,5044.6
XS Rating Curve= 0
Exp/Cntr=.3,.1

Type RM Length L Ch R = 1 ,10563.3 ,440.5,441.1,438.4
BEGIN DESCRIPTION:
Cross Section 10563.3
END DESCRIPTION:
XS GIS Cut Line= 2
      2988648.91     13847566.74      2988667.33      13847097.1
#Sta/Elev= 21
  4861.5     136  4876.5   135.9  4877.2  134.77  4955.5   133.4  4992.1  123.83
  4993.9   123.4  4999.5  122.63  5006.2  123.37  5008.6  123.79  5044.6  134.79
  5088.6  134.55  5130.6  134.33  5146.5   134.3  5161.5   133.6  5181.5   134.7
  5196.5   134.9  5221.5   134.2  5236.5   133.1  5251.5     133  5286.5     135
  5331.5   135.8
#Mann= 4 , 1 , 0
  4861.5     .06       0  4955.5     .04       0  5044.6     .06       0
  5088.6      .1       0
Bank Sta=4955.5,5044.6
XS Rating Curve= 0
Exp/Cntr=.3,.1

Type RM Length L Ch R = 1 ,10122.2 ,909.6,908.2,907.9
BEGIN DESCRIPTION:
Cross Section 10122.2-Interpolated
END DESCRIPTION:
XS GIS Cut Line= 4
      2988882.85       13848280.      2989068.85     13847876.26
      2989096.07     13847427.15      2989077.92     13846796.58
#Sta/Elev= 30
  4119.5   134.3  4465.5  134.74  4800.3   135.1  4830.4   136.8  4890.5   136.6
  4920.6   134.4  4935.6     134  4954.2   131.8    4972  126.13  4988.4  124.21
  4991.5  122.82    5002   122.6  5016.1  124.44    5043  132.74  5100.8   133.7
  5130.8   132.7  5160.8   132.7  5175.8     134  5205.8   134.3  5235.8     132
  5265.8   131.8  5310.9   134.9    5343   135.4  5386.7   135.4  5430.9     134
  5475.9   134.5  5505.9     133  5528.8  133.48  5637.9   133.7  5644.8   133.7
#Mann= 6 , 1 , 0
  4119.5      .2       0  4465.5      .1       0  4954.2     .04       0
    5043      .1       0  5528.8     .04       0  5637.9      .2       0
#XS Ineff= 2 , 0
       0                  5055.8       0   133.2
Permanent Ineff=
       F       F
Bank Sta=4954.2,5043
XS Rating Curve= 0
Exp/Cntr=.3,.1

Type RM Length L Ch R = 1 ,9214.0  ,643.2,662.3,647.5
BEGIN DESCRIPTION:
Cross Section 9214.0-Interpolated
END DESCRIPTION:
XS GIS Cut Line= 5
       2989908.1     13848107.62      2989998.83     13847921.62
      2990003.36     13847440.75      2989994.29     13847141.35
      2989953.46     13846624.19
#Sta/Elev= 30
  4336.2   134.1  4465.5  133.97  4824.4   134.1  4854.4   136.8  4871.8   136.8
  4954.2  131.73  4988.4  124.14  4991.5  122.75    5002  122.53  5016.1  124.37
  5019.4   127.1  5049.4   131.4  5109.5   132.6  5169.5   132.6  5199.5   136.8
  5214.5   137.7  5229.5   137.6  5259.5   134.8  5289.5   134.3  5319.6   131.6
  5364.7   134.6  5439.9   134.7  5485.1   132.9  5500.1     134  5528.8  133.83
  5545.2   132.8  5593.9   133.8  5621.8   131.9  5637.9  132.33  5842.3   132.2
#Mann= 6 , 1 , 0
  4336.2      .2       0  4465.5      .1       0  4954.2     .04       0
  5049.4      .1       0  5528.8     .04       0  5637.9      .2       0
#XS Ineff= 2 , 0
       0                  5109.5       0   132.6
Permanent Ineff=
       F       F
Bank Sta=4954.2,5049.4
XS Rating Curve= 0
Exp/Cntr=.5,.3

Type RM Length L Ch R = 1 ,8551.7  ,99,99,99
BEGIN DESCRIPTION:
Upstream Section of Bridge/Culvert/Weir
END DESCRIPTION:
XS GIS Cut Line= 3
      2990684.63     13848013.65       2990689.1      13847579.4
      2990728.84     13846753.83
#Sta/Elev= 30
  4465.5   145.7    4466   141.5    4561   137.3    4621   131.6  4795.9  133.65
  4876.9  132.01  4949.9   132.5  4954.2  131.68    4972  126.01  4988.4  124.09
  4991.5   122.7    5002  122.48  5016.1  124.32    5043  132.62  5048.3  133.23
  5066.6  132.71  5092.2  133.77  5154.1  132.68  5209.2  134.02  5288.1   134.7
  5333.1   133.3  5423.6   134.9  5483.6   133.2  5528.8  133.68  5556.2   132.9
  5581.2   133.3  5591.2   134.3  5621.2   139.4  5637.9  140.53  5726.3   141.7
#Mann= 6 , 1 , 0
  4465.5      .2       0  4465.5      .1       0  4954.2     .04       0
    5043      .1       0  5528.8     .04       0  5637.9      .2       0
#XS Ineff= 2 , 0
       0    4944   132.8    5050       0   132.8
Permanent Ineff=
       F       F
Bank Sta=4954.2,5043
XS Rating Curve= 0
Exp/Cntr=.5,.3