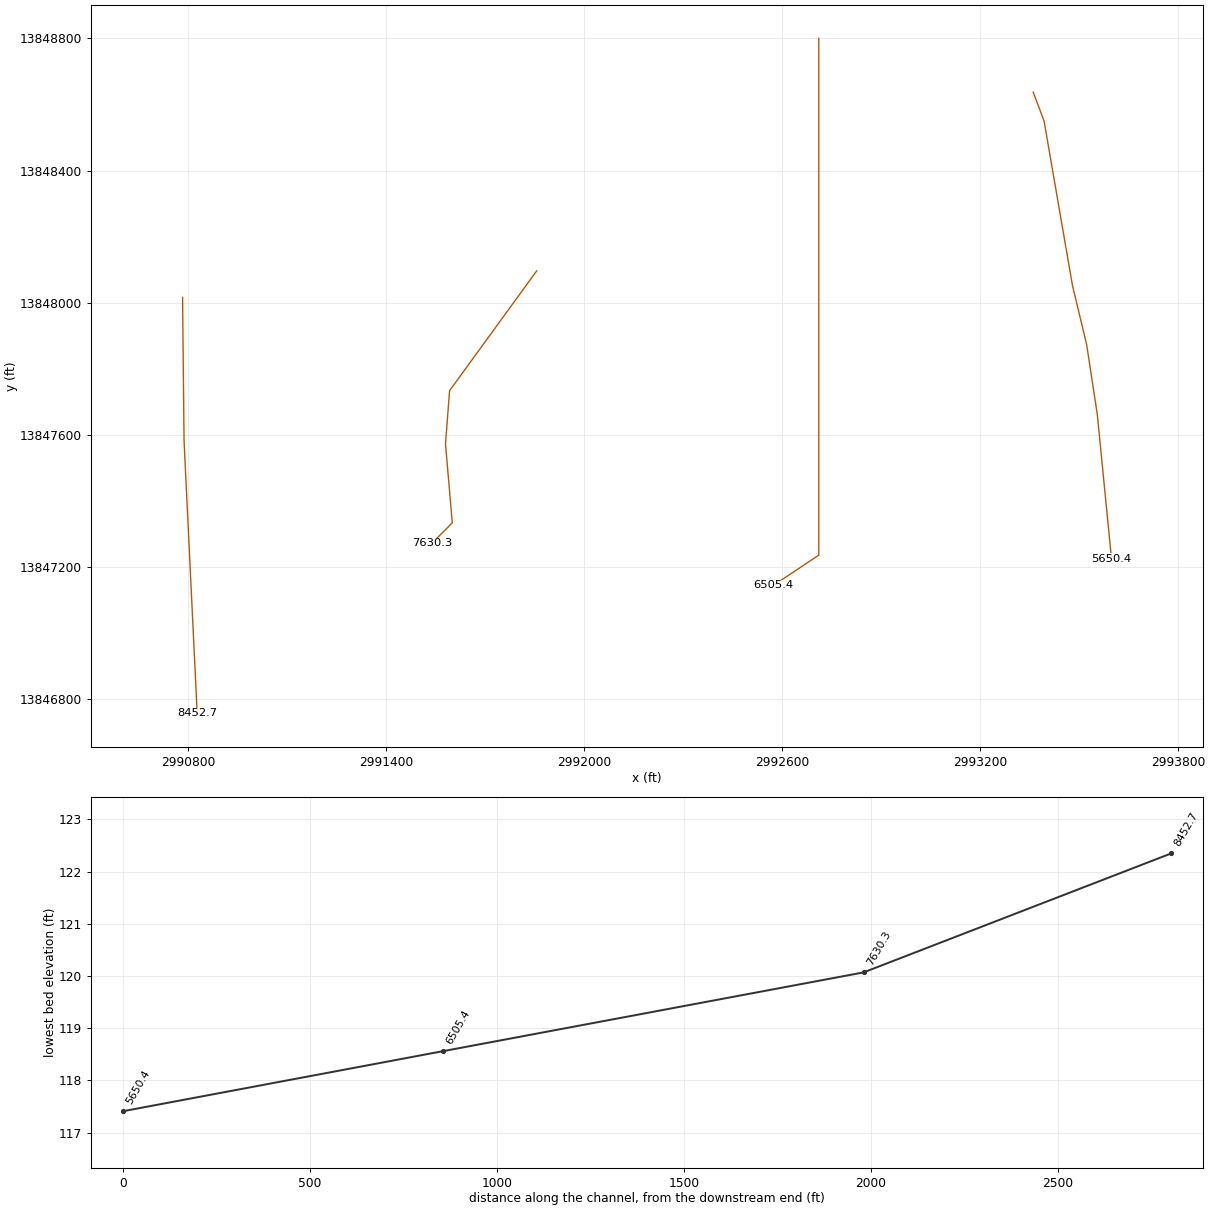
HEC-RAS study T101-03-00.PRJ: T101-03-00

--- T101-03-00.g01 (geometry) --- (continued)

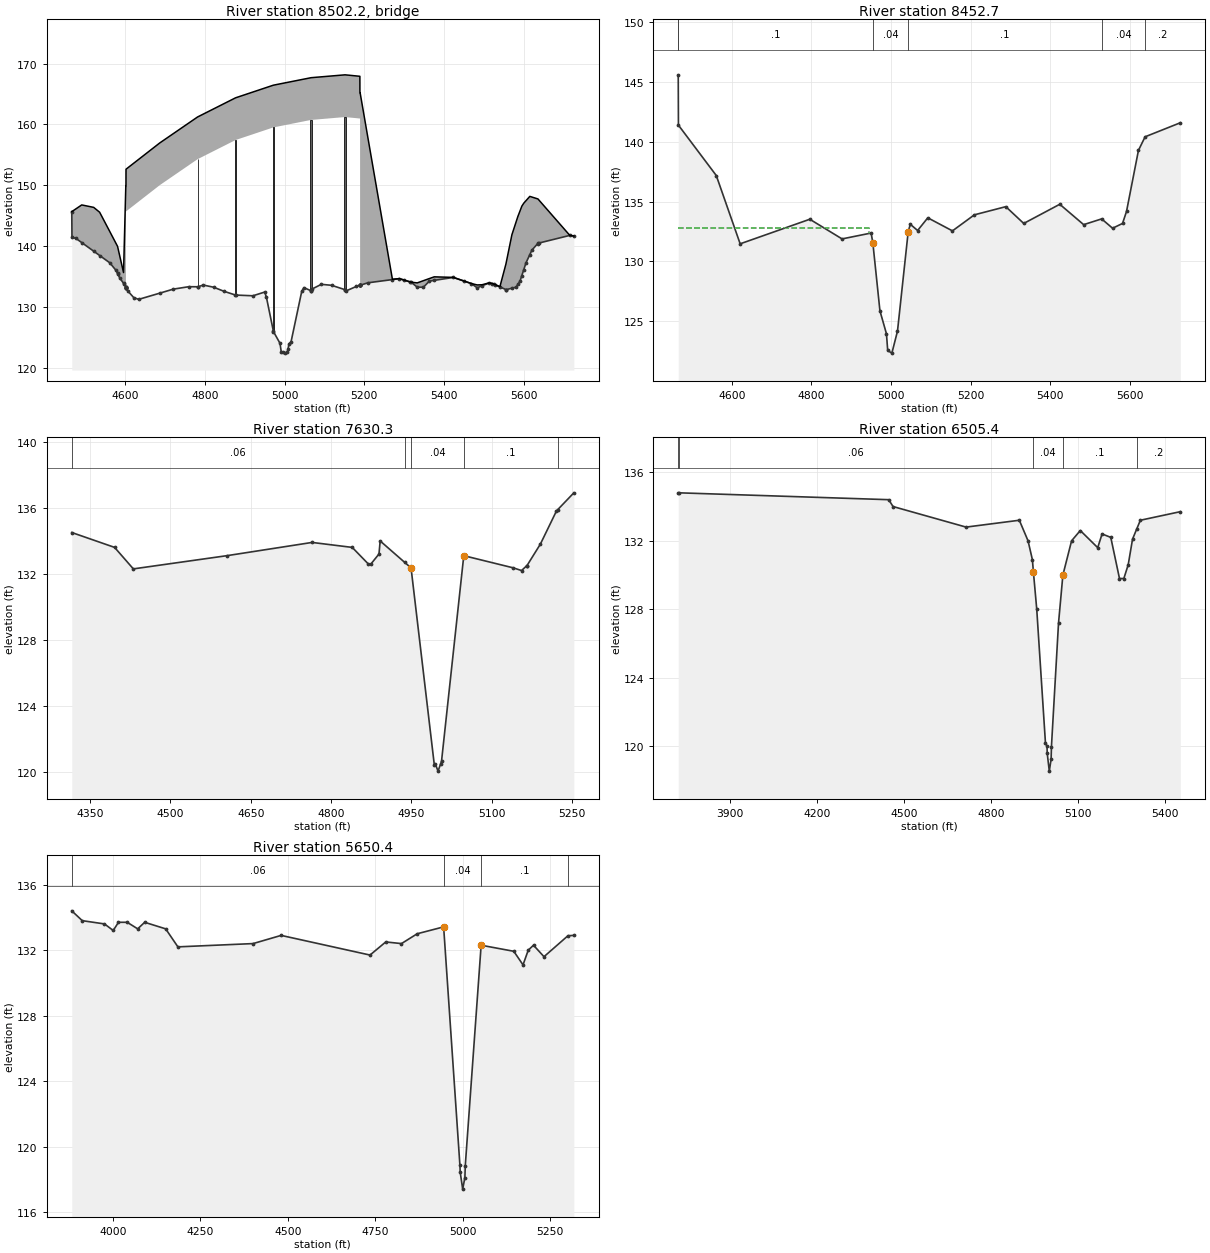
Type RM Length L Ch R = 3 ,8502.2  ,,,
BEGIN DESCRIPTION:
PEEK ROAD
Structure ID: T13-6
END DESCRIPTION:
Bridge Culvert--1,0,-1,-1, 0
Deck Dist Width WeirC Skew NumUp NumDn MinLoCord MaxHiCord MaxSubmerge Is_Ogee
10,79,2.6,0, 54, 54, , , .95, 0, 1,1,,
  4465.5    4466    4476  4490.5  4520.5  4535.5    4561    4576  4580.5    4586
  4595.5  4601.2  4601.4  4601.5 4601.59  4601.7  4686.4  4781.3  4876.9  4971.7
  5066.5  5151.8    5189 5189.11 5189.49  5189.6  5209.2  5270.7  5288.1  5318.1
  5333.1  5348.6  5363.6  5375.7  5423.6  5468.6  5483.6  5495.7  5513.6  5521.2
  5540.7  5555.7  5570.7  5581.2  5585.7  5591.2  5595.7  5600.7  5606.2  5615.7
  5621.2  5636.2  5716.2  5726.3
   145.7  145.72  146.16   146.8   146.4   145.6  142.43  140.56     140  138.42
   135.7  149.96  149.96  149.96  149.96  152.66  156.97  161.23  164.38  166.45
  167.68  168.15  167.91  165.21  165.21  165.21  157.81   134.6  134.71  134.11
  134.01  134.37  134.72     135  134.91  133.91  133.67   133.7  134.01  133.91
   133.4   137.1   141.9     144   144.9  145.83   146.6   147.1   147.5   148.2
  148.09  147.78   141.8   141.7
   145.7   141.5   141.3  140.62  139.21   138.5   137.3   136.1  135.56   134.8
  133.94  133.28  133.25  145.73  145.73  145.73  150.04   154.3  157.45  159.52
  160.75  161.22  160.98  160.98  160.98  133.62  134.02  134.55   134.7   134.1
   133.3   133.3   134.3  134.42   134.9   133.9   133.2  133.52     134   133.9
  133.34  132.91  133.13   133.3  133.75   134.3   135.2   136.2   137.3  138.63
   139.4   140.5   141.8   141.7
  4465.5    4466    4476  4490.5  4520.5  4535.5    4561    4576  4580.5    4586
  4595.5  4601.2  4601.4  4601.5 4601.59  4601.7  4686.4  4781.3  4876.9  4971.7
  5066.5  5151.8    5189 5189.11 5189.49  5189.6  5209.2  5270.7  5288.1  5318.1
  5333.1  5348.6  5363.6  5375.7  5423.6  5468.6  5483.6  5495.7  5513.6  5521.2
  5540.7  5555.7  5570.7  5581.2  5585.7  5591.2  5595.7  5600.7  5606.2  5615.7
  5621.2  5636.2  5716.2  5726.3
   145.7  145.72  146.16   146.8   146.4   145.6  142.43  140.56     140  138.42
   135.7  149.96  149.96  149.96  149.96  152.66  156.97  161.23  164.38  166.45
  167.68  168.15  167.91  165.21  165.21  165.21  157.81   134.6  134.71  134.11
  134.01  134.37  134.72     135  134.91  133.91  133.67   133.7  134.01  133.91
   133.4   137.1   141.9     144   144.9  145.83   146.6   147.1   147.5   148.2
  148.09  147.78   141.8   141.7
   145.6   141.4   141.2  140.52  139.11   138.4   137.2     136  135.46   134.7
  133.84  133.18  133.15  145.63  145.63  145.63  149.94   154.2  157.35  159.42
  160.65  161.12  160.88  160.88  160.88  133.52  133.92  134.45   134.6     134
   133.2   133.2   134.2  134.32   134.8   133.8   133.1  133.42   133.9   133.8
  133.24  132.81  133.03   133.2  133.65   134.2   135.1   136.1   137.2  138.53
   139.3   140.4   141.7   141.6
Pier Skew, UpSta & Num, DnSta & Num=  ,4782.3, 2 ,4782.3, 2 , 0 , 0 , 0 ,,
       1       1
  132.37  155.35
       1       1
  132.27  155.25
Pier Skew, UpSta & Num, DnSta & Num=  ,4876.9, 2 ,4876.9, 2 , 0 , 0 , 0 ,,
     3.5     3.5
  131.01  158.49
     3.5     3.5
  130.91  158.39
Pier Skew, UpSta & Num, DnSta & Num=  ,4972, 2 ,4972, 2 , 0 , 0 , 0 ,,
     3.5     3.5
  124.81  160.54
     3.5     3.5
  124.71  160.44
Pier Skew, UpSta & Num, DnSta & Num=  ,5066.6, 2 ,5066.6, 2 , 0 , 0 , 0 ,,
     3.5     3.5
  131.76  161.76
     3.5     3.5
  131.66  161.66
Pier Skew, UpSta & Num, DnSta & Num=  ,5151.8, 2 ,5151.8, 2 , 0 , 0 , 0 ,,
     3.5     3.5
  131.73  162.21
     3.5     3.5
  131.63  162.11
BR Coef= 1 , 1 , 0 ,1.25, 0 ,,,.8,0,2,0,
WSPro=,,,, 1 ,,,, 0 ,,,, 0 ,,,,-1 ,-1 ,-1 , 0 , 0 , 0 , 0 , 0
BR U #Sta/Elev= 100
  4465.5   145.7    4466   141.5    4476   141.3  4490.5  140.62  4520.5  139.21
  4535.5   138.5    4561   137.3    4576   136.1  4580.5  135.56    4581   135.5
    4586   134.8  4595.5  133.94    4596   133.9  4601.2  133.28 4601.31  133.26
  4601.4  133.25  4601.5  133.24 4601.59  133.23  4601.7  133.22 4601.81   133.2
    4606   132.7    4621   131.6  4633.4   131.3  4686.4  132.32  4720.4  132.98
  4759.4  133.38  4781.3  133.37  4782.3  133.37  4795.9  133.65    4822  133.29
  4847.6  132.63  4876.2  132.02  4876.9  132.01  4920.4  131.89  4949.9   132.5
  4954.2  131.68  4971.7  126.11    4972  126.01  4988.4  124.09  4991.5   122.7
  4995.4  122.69    5002  122.48  5006.4  122.65  5008.5  123.12  5011.1  124.03
  5016.1  124.32    5043  132.62  5048.3  133.23  5066.5  132.71  5066.6  132.71
    5068  132.97  5092.2  133.77  5117.9  133.61  5151.8  132.89  5152.3  132.84
  5154.1  132.68    5180  133.42 5188.89   133.6    5189   133.6 5189.11  133.61
  5189.4  133.61 5189.49  133.61  5189.6  133.62  5189.7  133.62  5209.2  134.02
  5270.7  134.55  5288.1   134.7  5300.7  134.45  5315.7  134.15  5318.1   134.1
  5333.1   133.3  5348.6   133.3  5363.6   134.3  5375.7  134.42  5423.6   134.9
  5450.7   134.3  5468.6   133.9  5483.6   133.2  5495.7  133.52  5513.6     134
  5521.2   133.9  5525.7  133.77  5528.8  133.68  5540.7  133.34  5555.7  132.91
  5556.2   132.9  5570.7  133.13  5581.2   133.3  5585.7  133.75  5591.2   134.3
  5595.7   135.2  5600.7   136.2  5606.2   137.3  5615.7  138.63  5621.2   139.4
  5635.7  140.46  5636.2   140.5  5637.9  140.53  5716.2   141.8  5726.3   141.7
BR U #Mann= 6
  4465.5      .2  4465.5      .1  4954.2     .04    5043      .1  5528.8     .04
  5637.9      .2
BR U Banks=4954.2,5043
BR D #Sta/Elev= 100
  4465.5   145.6    4466   141.4    4476   141.2  4490.5  140.52  4520.5  139.11
  4535.5   138.4    4561   137.2    4576     136  4580.5  135.46    4581   135.4
    4586   134.7  4595.5  133.84    4596   133.8  4601.2  133.18 4601.31  133.16
  4601.4  133.15  4601.5  133.14 4601.59  133.13  4601.7  133.12 4601.81   133.1
    4606   132.6    4621   131.5  4633.4   131.2  4686.4  132.22  4720.4  132.88
  4759.4  133.28  4781.3  133.27  4782.3  133.27  4795.9  133.55    4822  133.19
  4847.6  132.53  4876.2  131.92  4876.9  131.91  4920.4  131.79  4949.9   132.4
  4954.2  131.58  4971.7  126.01    4972  125.91  4988.4  123.99  4991.5   122.6
  4995.4  122.59    5002  122.38  5006.4  122.55  5008.5  123.02  5011.1  123.93
  5016.1  124.22    5043  132.52  5048.3  133.13  5066.5  132.61  5066.6  132.61
    5068  132.87  5092.2  133.67  5117.9  133.51  5151.8  132.79  5152.3  132.74
  5154.1  132.58    5180  133.32 5188.89   133.5    5189   133.5 5189.11  133.51
  5189.4  133.51 5189.49  133.51  5189.6  133.52  5189.7  133.52  5209.2  133.92
  5270.7  134.45  5288.1   134.6  5300.7  134.35  5315.7  134.05  5318.1     134
  5333.1   133.2  5348.6   133.2  5363.6   134.2  5375.7  134.32  5423.6   134.8
  5450.7   134.2  5468.6   133.8  5483.6   133.1  5495.7  133.42  5513.6   133.9
  5521.2   133.8  5525.7  133.67  5528.8  133.58  5540.7  133.24  5555.7  132.81
  5556.2   132.8  5570.7  133.03  5581.2   133.2  5585.7  133.65  5591.2   134.2
  5595.7   135.1  5600.7   136.1  5606.2   137.2  5615.7  138.53  5621.2   139.3
  5635.7  140.36  5636.2   140.4  5637.9  140.43  5716.2   141.7  5726.3   141.6
BR D #Mann= 6
  4465.5      .2  4465.5      .1  4954.2     .04    5043      .1  5528.8     .04
  5637.9      .2
BR D Banks=4954.2,5043
BC Design=,, 0 ,, 0 ,,,,,,
BC HTab HWMax=145.7

Type RM Length L Ch R = 1 ,8452.7  ,822.4,822.4,822.4
BEGIN DESCRIPTION:
Downstream Section of Bridge/Culvert/Weir
END DESCRIPTION:
XS GIS Cut Line= 3
      2990783.61     13848015.73      2990788.08     13847581.48
      2990827.82     13846755.91
#Sta/Elev= 30
  4465.5  145.57    4466  141.37    4561  137.17    4621  131.47  4795.9  133.52
  4876.9  131.88  4949.9  132.37  4954.2  131.55    4972  125.88  4988.4  123.96
  4991.5  122.57    5002  122.35  5016.1  124.19    5043  132.49  5048.3   133.1
  5066.6  132.58  5092.2  133.64  5154.1  132.55  5209.2  133.89  5288.1  134.57
  5333.1  133.17  5423.6  134.77  5483.6  133.07  5528.8  133.55  5556.2  132.77
  5581.2  133.17  5591.2  134.17  5621.2  139.27  5637.9   140.4  5726.3  141.57
#Mann= 6 , 1 , 0
  4465.5      .2       0  4465.5      .1       0  4954.2     .04       0
    5043      .1       0  5528.8     .04       0  5637.9      .2       0
#XS Ineff= 2 , 0
       0    4944   132.8    5050       0   132.8
Permanent Ineff=
       F       F
Bank Sta=4954.2,5043
XS Rating Curve= 0
Exp/Cntr=.5,.3

Type RM Length L Ch R = 1 ,7630.3  ,1128.5,1124.9,1119.4
BEGIN DESCRIPTION:
Cross Section 7630.3
END DESCRIPTION:
XS GIS Cut Line= 5
      2991856.49     13848096.06      2991592.49     13847733.07
      2991580.12     13847572.19      2991600.74     13847332.93
      2991538.87     13847271.06
#Sta/Elev= 26
  4315.7   134.5  4395.7   133.6  4430.7   132.3  4605.7   133.1  4764.6   133.9
  4839.6   133.6  4869.6   132.6  4874.6   132.6  4889.6   133.2  4891.8  133.99
  4937.4   132.7  4949.5  132.36  4992.9  120.46    4995  120.49  4999.9  120.07
  5004.9  120.52  5006.4  120.66    5048   133.1  5140.8  132.36  5155.9   132.2
  5165.9   132.5  5166.1   132.5  5191.1   133.8  5221.1   135.8  5223.7  135.89
  5253.6   136.9
#Mann= 5 , 1 , 0
  4315.7     .06       0  4937.4      .1       0  4949.5     .04       0
    5048      .1       0  5223.7      .2       0
Bank Sta=4949.5,5048
XS Rating Curve= 0
Exp/Cntr=.3,.1

Type RM Length L Ch R = 1 ,6505.4  ,852.7,855,860.9
BEGIN DESCRIPTION:
Cross Section 6505.4-Interpolated
END DESCRIPTION:
XS GIS Cut Line= 4
      2992711.11     13848800.26      2992711.11     13847508.69
      2992711.11     13847235.18      2992574.36     13847144.01
#Sta/Elev= 30
  3722.1   134.8  3725.1   134.8    4447   134.4    4462     134  4713.6   132.8
    4897   133.2    4927     132    4942   130.9  4945.4   130.2    4957     128
    4987   120.2  4992.3  120.01  4993.1   119.6  5000.2  118.56  5006.5  119.26
  5007.6  119.99    5032   127.2    5047     130    5077     132    5107   132.6
    5167   131.6    5182   132.4    5212   132.2    5242   129.8    5257   129.8
    5272   130.6    5287   132.1  5301.4  132.69  5313.9   133.2  5451.5   133.7
#Mann= 5 , 1 , 0
  3722.1      .2       0  3725.1     .06       0  4945.4     .04       0
    5047      .1       0  5301.4      .2       0
Bank Sta=4945.4,5047
XS Rating Curve= 0
Exp/Cntr=.3,.1

Type RM Length L Ch R = 1 ,5650.4  ,507.4,504.7,499.3
BEGIN DESCRIPTION:
Cross Section 5650.4
END DESCRIPTION:
XS GIS Cut Line= 6
      2993360.59     13848637.31      2993393.59     13848549.77
      2993479.59     13848051.74      2993522.58     13847872.59
      2993554.83      13847661.2      2993597.82     13847224.08
#Sta/Elev= 30
  3881.9   134.4  3911.9   133.8  3975.5   133.6  4000.5   133.2  4015.5   133.7
  4040.5   133.7  4070.5   133.3  4090.5   133.7  4150.5   133.3  4185.5   132.2
  4400.5   132.4  4480.9   132.9  4735.1   131.7  4780.1   132.5  4825.1   132.4
  4870.1     133  4945.7  133.42  4992.3  118.86  4993.1  118.45  5000.2  117.41
  5006.5  118.11  5007.6  118.84    5053   132.3  5146.4  131.93  5172.8   131.1
  5187.8     132  5202.8   132.3  5232.8   131.6  5301.4  132.88  5318.2   132.9
#Mann= 4 , 1 , 0
  3881.9     .06       0  4945.7     .04       0    5053      .1       0
  5301.4      .2       0
Bank Sta=4945.7,5053
XS Rating Curve= 0
Exp/Cntr=.3,.1