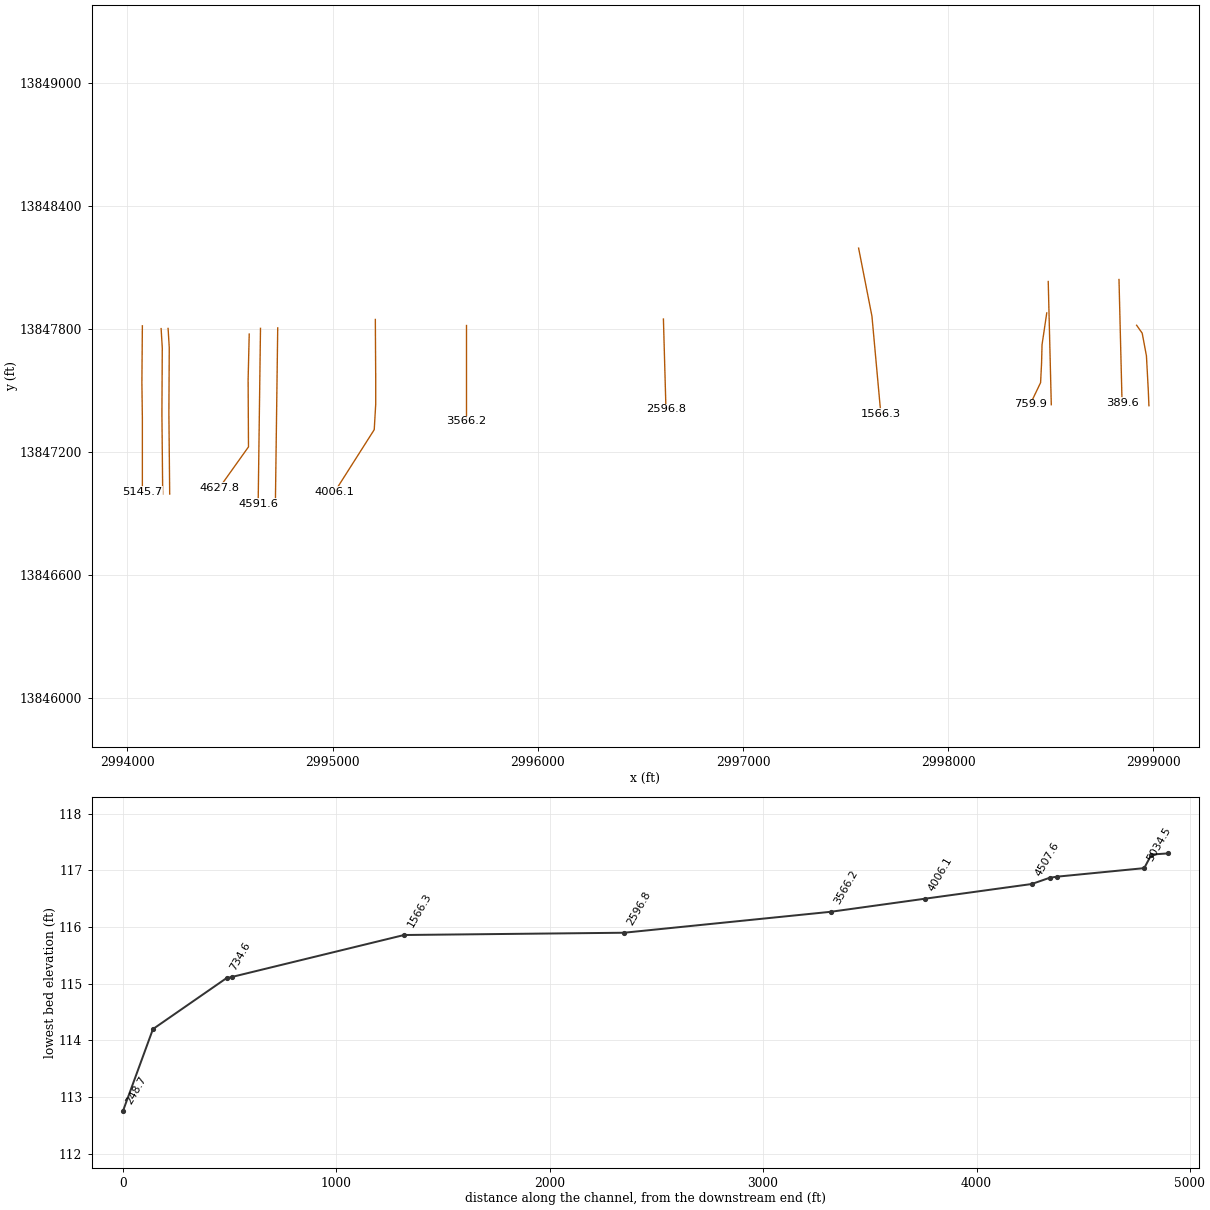
HEC-RAS study T101-03-00.PRJ: T101-03-00

--- T101-03-00.g01 (geometry) --- (continued)

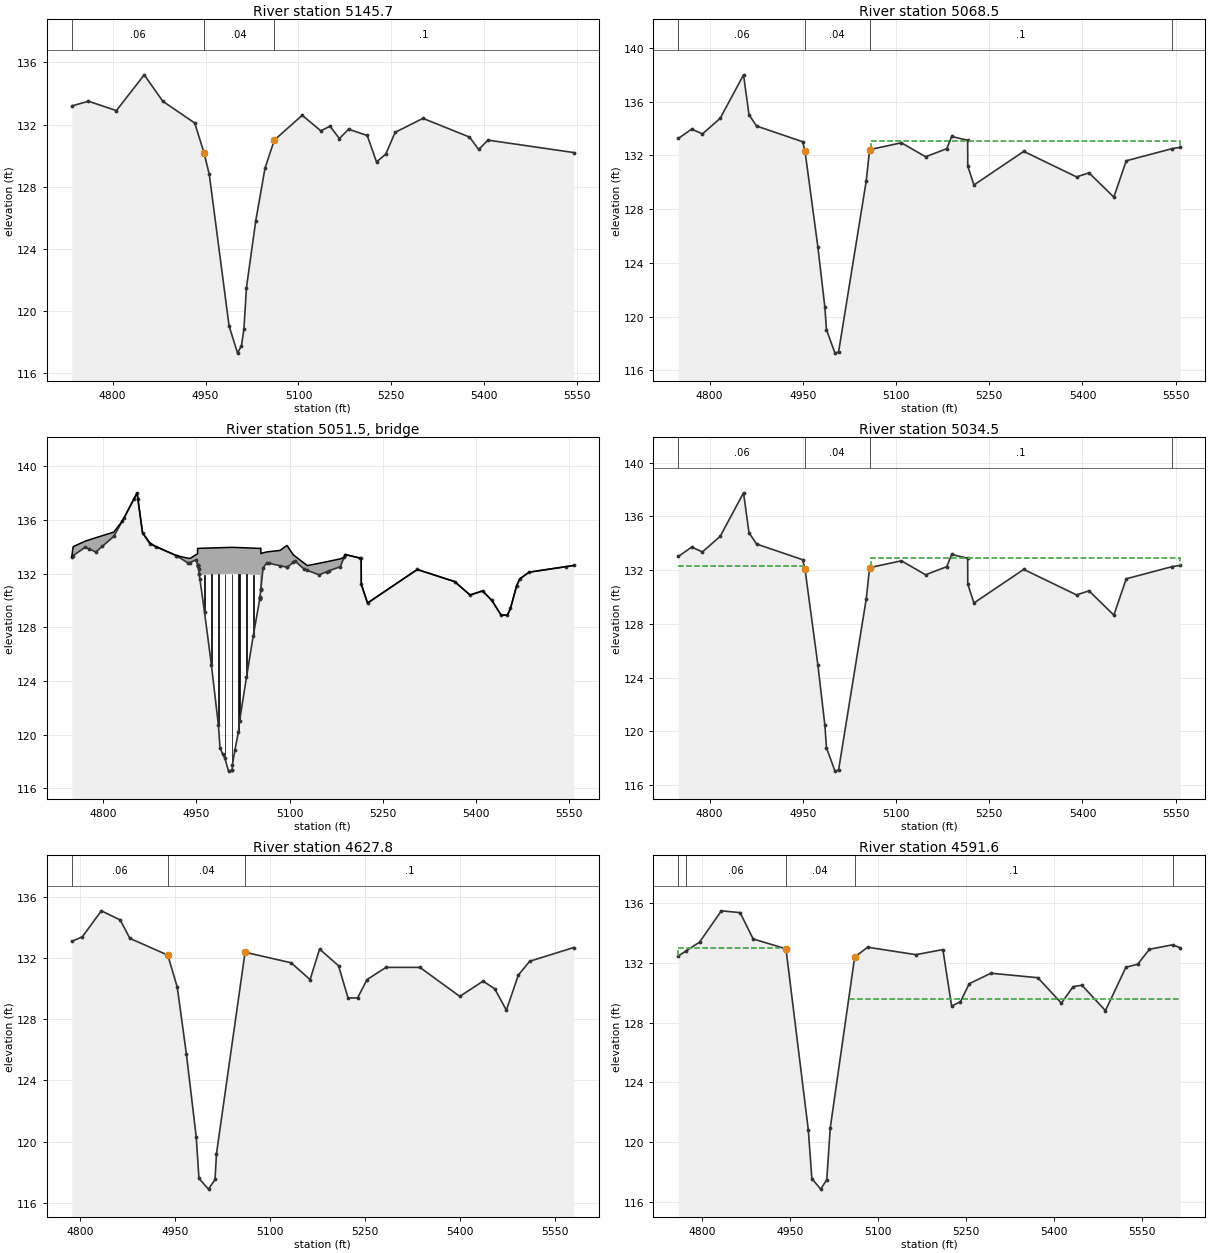
Type RM Length L Ch R = 1 ,5145.7  ,76.4,77.2,78.3
BEGIN DESCRIPTION:
Cross Section 5145.7-Interpolated
END DESCRIPTION:
XS GIS Cut Line= 4
       2994072.7     13847817.37      2994070.38     13847540.97
       2994072.7     13847364.45       2994072.7     13847006.76
#Sta/Elev= 30
    4734   133.2    4761   133.5    4806   132.9    4851   135.2    4881   133.5
  4932.5   132.1  4947.4   130.2    4956   128.8    4988  119.04  5001.7   117.3
    5008  117.79    5012  118.88    5016   121.5    5031   125.8    5046   129.2
    5061     131    5106   132.6    5136   131.6    5151   131.9    5166   131.1
    5181   131.7    5211   131.3    5226   129.6    5241   130.1    5256   131.5
    5301   132.4    5376   131.2    5391   130.4    5406     131  5544.6   130.2
#Mann= 3 , 1 , 0
    4734     .06       0  4947.4     .04       0    5061      .1       0
Bank Sta=4947.4,5061
XS Rating Curve= 0
Exp/Cntr=.5,.3

Type RM Length L Ch R = 1 ,5068.5  ,34,34,34
BEGIN DESCRIPTION:
Upstream Section of Bridge/Culvert/Weir
END DESCRIPTION:
XS GIS Cut Line= 4
      2994164.05     13847803.92      2994169.74     13847710.17
      2994167.93     13847389.62      2994171.84     13846996.02
#Sta/Elev= 30
  4749.4  133.26  4771.1  133.96  4788.3   133.6  4816.9  134.76  4854.5     138
  4863.3  135.03  4875.4  134.19  4949.6  133.02  4953.4  132.33  4974.2  125.17
  4985.4   120.7    4988  119.02  5001.7  117.28  5007.5  117.37    5052   130.1
  5057.4  132.43  5108.6  132.94  5147.5   131.9  5181.6   132.5  5189.5  133.41
  5215.2  133.13  5215.4   131.2  5225.4   129.8  5305.5   132.3  5390.5   130.4
  5410.5   130.7  5450.5   128.9  5470.5   131.6  5544.7  132.51  5557.5   132.6
#Mann= 4 , 1 , 0
  4749.4     .06       0  4953.4     .04       0  5057.4      .1       0
  5544.7      .2       0
#XS Ineff= 2 , 0
       0  4952.4   132.5    5060       0   133.1
Permanent Ineff=
       F       F
Bank Sta=4953.4,5057.4
XS Rating Curve= 0
Exp/Cntr=.5,.3

Type RM Length L Ch R = 3 ,5051.5  ,,,
BEGIN DESCRIPTION:
INTERSTATE 10-FRONTAGE ROAD
Structure ID: T13-5
END DESCRIPTION:
Bridge Culvert--1,0,-1,-1, 0
Deck Dist Width WeirC Skew NumUp NumDn MinLoCord MaxHiCord MaxSubmerge Is_Ogee
10,14,2.6,0, 51, 51, , , .95, 0, 1,1,,
  4749.4  4751.6  4771.1  4788.3  4816.9  4830.9  4854.5  4863.3  4875.4  4884.6
  4918.2  4937.2  4940.1  4949.6 4951.89    4952  4953.4  4954.6  4955.6    5008
 5052.19  5052.3  5053.7 5053.81  5057.4  5063.7  5084.5  5095.8    5106  5108.6
  5123.1  5128.5  5147.5  5181.6  5187.7  5189.5  5215.2  5215.4  5225.4  5305.5
  5365.5  5390.5  5410.5  5425.5  5440.5  5450.5  5455.5  5465.5  5470.5  5485.5
  5557.5
  133.26     134  134.41  134.67  135.08  135.92  138.01  135.04  134.27  134.01
  133.33  133.13  133.13  133.41  133.47  133.87  133.87  133.87  133.88  133.95
  133.87  133.87  133.89  133.49  133.54  133.61  133.72  134.09  133.39   133.3
  132.78  132.59  132.76  133.09  133.21  133.42  133.13   131.2   129.8   132.3
   131.4   130.4   130.7     130   128.9   128.9   129.4   131.1   131.6   132.1
   132.6
  133.26  133.33  133.96   133.6  134.76  135.91     138  135.03  134.19     134
  133.32  132.76  132.82  133.02   132.6  132.58  132.33  131.93  131.91  131.98
   131.9  130.23  130.83  130.88  132.43   132.8  132.58  132.47  132.84  132.94
  132.33  132.23   131.9   132.5   133.2  133.41  133.13   131.2   129.8   132.3
   131.4   130.4   130.7     130   128.9   128.9   129.4   131.1   131.6   132.1
   132.6
  4749.4  4751.6  4771.1  4788.3  4816.9  4830.9  4854.5  4863.3  4875.4  4884.6
  4918.2  4937.2  4940.1  4949.6 4951.89    4952  4953.4  4954.6  4955.6    5008
 5052.19  5052.3  5053.7 5053.81  5057.4  5063.7  5084.5  5095.8    5106  5108.6
  5123.1  5128.5  5147.5  5181.6  5187.7  5189.5  5215.2  5215.4  5225.4  5305.5
  5365.5  5390.5  5410.5  5425.5  5440.5  5450.5  5455.5  5465.5  5470.5  5485.5
  5557.5
  133.26     134  134.41  134.67  135.08  135.92  138.01  135.04  134.27  134.01
  133.33  133.13  133.13  133.41  133.47  133.87  133.87  133.87  133.88  133.95
  133.87  133.87  133.89  133.49  133.54  133.61  133.72  134.09  133.39   133.3
  132.78  132.59  132.76  133.09  133.21  133.42  133.13   131.2   129.8   132.3
   131.4   130.4   130.7     130   128.9   128.9   129.4   131.1   131.6   132.1
   132.6
  133.02  133.09  133.72  133.36  134.52  135.67  137.76  134.79  133.95  133.76
  133.08  132.52  132.58  132.78  132.36  132.34  132.09  131.69  131.67  131.74
  131.66  129.99  130.59  130.64  132.19  132.56  132.34  132.23   132.6   132.7
  132.09  131.99  131.66  132.26  132.96  133.17  132.89  130.96  129.56  132.06
  131.16  130.16  130.46  129.76  128.66  128.66  129.16  130.86  131.36  131.86
  132.36
Pier Skew, UpSta & Num, DnSta & Num=  ,4963.1, 2 ,4963.1, 2 , 0 , 0 , 0 ,,
       1       1
  127.93  132.92
       1       1
  127.69  132.68
Pier Skew, UpSta & Num, DnSta & Num=  ,4974.2, 2 ,4974.2, 2 , 0 , 0 , 0 ,,
       1       1
  123.97  132.93
       1       1
  123.73  132.69
Pier Skew, UpSta & Num, DnSta & Num=  ,4985.4, 2 ,4985.4, 2 , 0 , 0 , 0 ,,
       1       1
  119.38  132.95
       1       1
  119.14  132.71
Pier Skew, UpSta & Num, DnSta & Num=  ,4995.8, 2 ,4995.8, 2 , 0 , 0 , 0 ,,
       1       1
  117.17  132.96
       1       1
  116.93  132.72
Pier Skew, UpSta & Num, DnSta & Num=  ,5007.5, 2 ,5007.5, 2 , 0 , 0 , 0 ,,
       1       1
  116.36  132.98
       1       1
  116.12  132.74
Pier Skew, UpSta & Num, DnSta & Num=  ,5017.6, 2 ,5017.6, 2 , 0 , 0 , 0 ,,
       1       1
  119.07  132.96
       1       1
  118.83  132.72
Pier Skew, UpSta & Num, DnSta & Num=  ,5019.4, 2 ,5019.4, 2 , 0 , 0 , 0 ,,
       1       1
  119.77  132.96
       1       1
  119.53  132.72
Pier Skew, UpSta & Num, DnSta & Num=  ,5030.6, 2 ,5030.6, 2 , 0 , 0 , 0 ,,
       1       1
  123.12  132.94
       1       1
  122.88   132.7
Pier Skew, UpSta & Num, DnSta & Num=  ,5041.4, 2 ,5041.4, 2 , 0 , 0 , 0 ,,
       1       1
   126.2  132.92
       1       1
  125.96  132.68
Abutment Skew #Up #Dn= , 2 , 2
  4954.4  4955.6
  131.93   131.6
  4954.4  4955.6
  131.69  131.36
BR Coef= 1 , 1 , 0 ,1.25, 0 ,,,.8,0,2,0,
WSPro=,,,, 1 ,,,, 0 ,,,, 0 ,,,,-1 ,-1 ,-1 , 0 , 0 , 0 , 0 , 0
BR U #Sta/Elev= 84
  4749.4  133.26  4751.6  133.33  4771.1  133.96  4777.4  133.83  4788.3   133.6
  4798.6  134.02  4816.9  134.76  4830.9  135.91  4833.2   136.1  4849.2  137.53
  4854.5     138  4855.8  137.56  4863.3  135.03  4875.4  134.19  4884.6     134
  4917.7  133.33  4918.2  133.32  4937.2  132.76  4940.1  132.82  4949.6  133.02
  4951.8  132.62 4951.89   132.6    4952  132.58 4952.11  132.56  4953.4  132.33
 4954.51  131.96  4954.6  131.93  4955.6   131.6  4963.1  129.11  4974.2  125.17
  4985.4   120.7    4988  119.02  4992.2  118.56  4995.8  118.25  5001.7  117.28
  5006.5  117.35  5007.5  117.37    5008  117.77    5012  118.86  5017.6  120.19
  5019.4  120.99  5030.6  124.27  5041.4  127.34    5052   130.1  5052.1  130.14
 5052.19  130.18  5052.3  130.23  5052.4  130.27 5053.59  130.79  5053.7  130.83
 5053.81  130.88  5057.4  132.43  5063.7   132.8  5066.5  132.77  5084.5  132.58
  5095.8  132.47  5096.3  132.46    5106  132.84  5108.6  132.94  5123.1  132.33
  5128.5  132.23  5147.5   131.9  5160.3  132.14  5163.7  132.21  5181.6   132.5
  5187.7   133.2  5189.5  133.41  5213.9  133.14  5215.2  133.13  5215.4   131.2
  5225.4   129.8  5305.5   132.3  5365.5   131.4  5390.5   130.4  5410.5   130.7
  5425.5     130  5440.5   128.9  5450.5   128.9  5455.5   129.4  5465.5   131.1
  5470.5   131.6  5485.5   132.1  5544.7  132.51  5557.5   132.6
BR U #Mann= 4
  4749.4     .06  4953.4     .04  5057.4      .1  5544.7      .2
BR U Banks=4953.4,5057.4
BR D #Sta/Elev= 84
  4749.4  133.02  4751.6  133.09  4771.1  133.72  4777.4  133.59  4788.3  133.36
  4798.6  133.78  4816.9  134.52  4830.9  135.67  4833.2  135.86  4849.2  137.29
  4854.5  137.76  4855.8  137.32  4863.3  134.79  4875.4  133.95  4884.6  133.76
  4917.7  133.09  4918.2  133.08  4937.2  132.52  4940.1  132.58  4949.6  132.78
  4951.8  132.38 4951.89  132.36    4952  132.34 4952.11  132.32  4953.4  132.09
 4954.51  131.72  4954.6  131.69  4955.6  131.36  4963.1  128.87  4974.2  124.93
  4985.4  120.46    4988  118.78  4992.2  118.32  4995.8  118.01  5001.7  117.04
  5006.5  117.11  5007.5  117.13    5008  117.53    5012  118.62  5017.6  119.95
  5019.4  120.75  5030.6  124.03  5041.4   127.1    5052  129.86  5052.1   129.9
 5052.19  129.94  5052.3  129.99  5052.4  130.03 5053.59  130.55  5053.7  130.59
 5053.81  130.64  5057.4  132.19  5063.7  132.56  5066.5  132.53  5084.5  132.34
  5095.8  132.23  5096.3  132.22    5106   132.6  5108.6   132.7  5123.1  132.09
  5128.5  131.99  5147.5  131.66  5160.3   131.9  5163.7  131.97  5181.6  132.26
  5187.7  132.96  5189.5  133.17  5213.9   132.9  5215.2  132.89  5215.4  130.96
  5225.4  129.56  5305.5  132.06  5365.5  131.16  5390.5  130.16  5410.5  130.46
  5425.5  129.76  5440.5  128.66  5450.5  128.66  5455.5  129.16  5465.5  130.86
  5470.5  131.36  5485.5  131.86  5544.7  132.27  5557.5  132.36
BR D #Mann= 4
  4749.4     .06  4953.4     .04  5057.4      .1  5544.7      .2
BR D Banks=4953.4,5057.4
BC Design=,, 0 ,, 0 ,,,,,,
BC HTab HWMax=138

Type RM Length L Ch R = 1 ,5034.5  ,406.7,406.7,406.7
BEGIN DESCRIPTION:
Downstream Section of Bridge/Culvert/Weir
END DESCRIPTION:
XS GIS Cut Line= 4
      2994198.04     13847804.65      2994203.74     13847710.89
      2994201.93     13847390.34      2994205.84     13846996.74
#Sta/Elev= 30
  4749.4  133.02  4771.1  133.72  4788.3  133.36  4816.9  134.52  4854.5  137.76
  4863.3  134.79  4875.4  133.95  4949.6  132.78  4953.4  132.09  4974.2  124.93
  4985.4  120.46    4988  118.78  5001.7  117.04  5007.5  117.13    5052  129.86
  5057.4  132.19  5108.6   132.7  5147.5  131.66  5181.6  132.26  5189.5  133.17
  5215.2  132.89  5215.4  130.96  5225.4  129.56  5305.5  132.06  5390.5  130.16
  5410.5  130.46  5450.5  128.66  5470.5  131.36  5544.7  132.27  5557.5  132.36
#Mann= 4 , 1 , 0
  4749.4     .06       0  4953.4     .04       0  5057.4      .1       0
  5544.7      .2       0
#XS Ineff= 2 , 0
       0  4952.4   132.3    5060       0   132.9
Permanent Ineff=
       F       F
Bank Sta=4953.4,5057.4
XS Rating Curve= 0
Exp/Cntr=.5,.3

Type RM Length L Ch R = 1 ,4627.8  ,38.1,36.2,35.8
BEGIN DESCRIPTION:
Cross Section 4627.8-Interpolated
END DESCRIPTION:
XS GIS Cut Line= 4
       2994593.4      13847777.1      2994588.04     13847553.77
      2994589.83     13847226.81      2994448.68     13847028.49
#Sta/Elev= 30
  4786.4   133.1  4803.1   133.4  4833.1   135.1  4863.1   134.5  4878.2   133.3
  4938.2   132.2  4953.2   130.1  4967.7   125.7  4983.2   120.3  4987.5  117.59
  5002.6  116.89  5012.9  117.52  5015.2  119.21  5060.4  132.39  5133.2   131.7
  5163.2   130.6  5178.2   132.6  5208.2   131.5  5223.2   129.4  5238.2   129.4
  5253.2   130.6  5283.2   131.4  5336.8   131.4  5399.9   129.5  5436.7   130.5
  5455.1     130  5473.5   128.6  5492.5   130.9  5510.4   131.8  5580.2   132.7
#Mann= 3 , 1 , 0
  4786.4     .06       0  4938.2     .04       0  5060.4      .1       0
Bank Sta=4938.2,5060.4
XS Rating Curve= 0
Exp/Cntr=.5,.3

Type RM Length L Ch R = 1 ,4591.6  ,84,84,84
BEGIN DESCRIPTION:
Upstream Section of Bridge/Culvert/Weir
END DESCRIPTION:
XS GIS Cut Line= 2
      2994648.35     13847805.15      2994636.99     13846950.03
#Sta/Elev= 30
  4759.9  132.45  4772.5  132.77  4796.3  133.38  4833.3  135.47  4865.3  135.35
  4887.5  133.59  4943.4  132.93  4981.4  120.85  4987.5  117.57  5002.6  116.87
  5012.9   117.5  5018.8  120.95  5060.4  132.37  5082.4  133.04  5164.7  132.54
  5210.7  132.88  5225.6   129.1  5240.6   129.4  5255.6   130.6  5292.5   131.3
  5372.5     131  5412.5   129.3  5432.5   130.4  5447.5   130.5  5487.5   128.8
  5522.5   131.7  5542.5   131.9  5562.5   132.9    5602   133.2  5615.1     133
#Mann= 5 , 1 , 0
  4759.9      .2       0  4772.5     .06       0  4943.4     .04       0
  5060.4      .1       0    5602      .2       0
#XS Ineff= 2 , 0
       0    4933     133  5050.3       0   129.6
Permanent Ineff=
       F       F
Bank Sta=4943.4,5060.4
XS Rating Curve= 0
Exp/Cntr=.5,.3

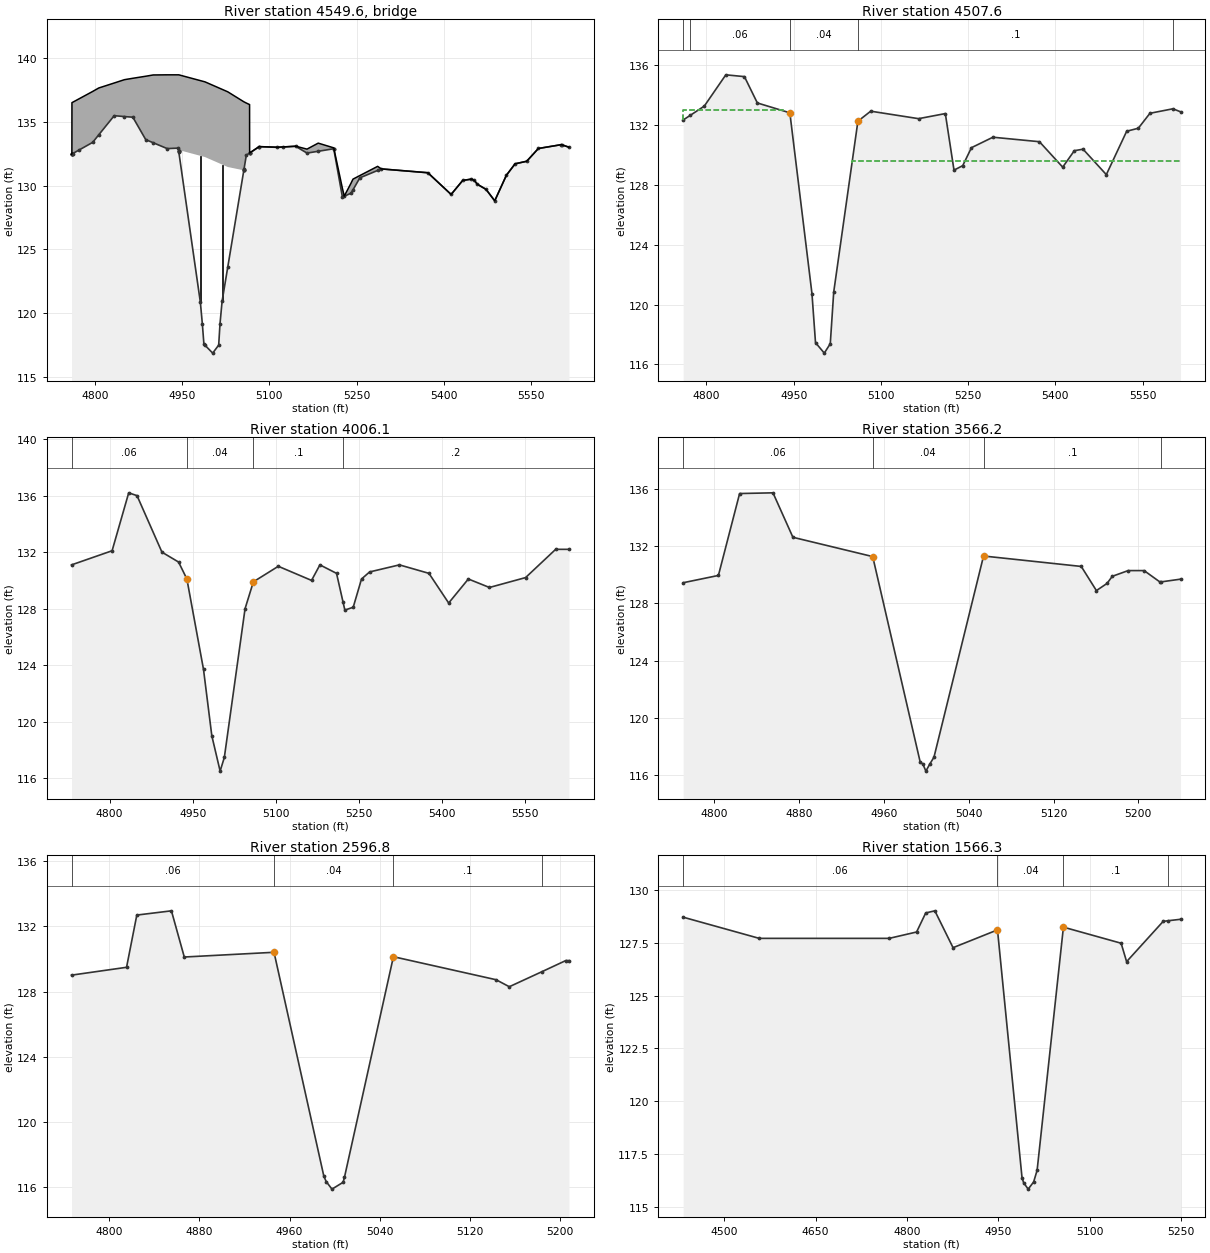
Type RM Length L Ch R = 3 ,4549.6  ,,,
BEGIN DESCRIPTION:
ELROD ROAD-FRONTAGE ROAD
Structure ID: T13-4
END DESCRIPTION:
Bridge Culvert--1,0,-1,-1, 0
Deck Dist Width WeirC Skew NumUp NumDn MinLoCord MaxHiCord MaxSubmerge Is_Ogee
10,64,2.6,0, 47, 47, , , .95, 0, 1,1,,
  4759.9 4760.49  4760.6  4796.3  4806.7  4833.3  4850.8  4865.3  4887.5  4900.3
  4924.4  4943.4 4944.11  4944.3  4989.3  5028.5  5056.1  5060.4    5066 5066.11
  5082.4  5113.8  5145.2  5164.7    5184  5210.7  5225.6  5228.8  5240.6  5243.8
  5255.6  5286.2  5292.5  5372.5  5412.5  5432.5  5447.5  5452.5  5457.5  5472.5
  5487.5  5507.5  5522.5  5542.5  5562.5    5602  5615.1
  132.45  132.49  136.49  137.37  137.64  138.03  138.29   138.4  138.56  138.66
  138.67  138.67  138.67  138.67  138.12  137.34  136.56  136.46  136.34  132.55
  133.05     133  133.08  132.85  133.32  132.95  129.78  129.17   130.2   130.5
  130.78   131.5   131.3     131   129.3   130.4   130.5   130.4   130.1   129.7
   128.8   130.8   131.7   131.9   132.9   133.2     133
  132.45  132.47  132.47  133.38  133.97  135.47   135.4  135.35  133.59  133.35
  132.89  132.93   132.7  132.78  132.23  131.45  131.19  132.37  132.54  132.54
  133.04  132.99  133.07  132.54  132.68  132.88   129.1  129.16   129.4  129.66
   130.6  131.18   131.3     131   129.3   130.4   130.5   130.4   130.1   129.7
   128.8   130.8   131.7   131.9   132.9   133.2     133
  4759.9 4760.49  4760.6  4796.3  4806.7  4833.3  4850.8  4865.3  4887.5  4900.3
  4924.4  4943.4 4944.11  4944.3  4989.3  5028.5  5056.1  5060.4    5066 5066.11
  5082.4  5113.8  5145.2  5164.7    5184  5210.7  5225.6  5228.8  5240.6  5243.8
  5255.6  5286.2  5292.5  5372.5  5412.5  5432.5  5447.5  5452.5  5457.5  5472.5
  5487.5  5507.5  5522.5  5542.5  5562.5    5602  5615.1
  132.45  132.49  136.49  137.37  137.64  138.03  138.29   138.4  138.56  138.66
  138.67  138.67  138.67  138.67  138.12  137.34  136.56  136.46  136.34  132.55
  133.05     133  133.08  132.85  133.32  132.95  129.78  129.17   130.2   130.5
  130.78   131.5   131.3     131   129.3   130.4   130.5   130.4   130.1   129.7
   128.8   130.8   131.7   131.9   132.9   133.2     133
  132.35  132.37  132.37  133.28  133.87  135.37   135.3  135.25  133.49  133.25
  132.79  132.83   132.6  132.68  132.13  131.35  131.09  132.27  132.44  132.44
  132.94  132.89  132.97  132.44  132.58  132.78     129  129.06   129.3  129.56
   130.5  131.08   131.2   130.9   129.2   130.3   130.4   130.3     130   129.6
   128.7   130.7   131.6   131.8   132.8   133.1   132.9
Pier Skew, UpSta & Num, DnSta & Num=  ,4981.4, 2 ,4981.4, 2 , 0 , 0 , 0 ,,
     1.4     1.4
   119.5  133.34
     1.4     1.4
   119.4  133.24
Pier Skew, UpSta & Num, DnSta & Num=  ,5018.8, 2 ,5018.8, 2 , 0 , 0 , 0 ,,
     1.4     1.4
  119.61  132.65
     1.4     1.4
  119.51  132.55
BR Coef= 1 , 1 , 0 ,1.25, 0 ,,,.8,0,2,0,
WSPro=,,,, 1 ,,,, 0 ,,,, 0 ,,,,-1 ,-1 ,-1 , 0 , 0 , 0 , 0 , 0
BR U #Sta/Elev= 67
  4759.9  132.45 4760.49  132.47  4760.6  132.47 4760.71  132.47  4761.8   132.5
  4772.5  132.77  4796.3  133.38  4806.7  133.97  4833.3  135.47  4850.8   135.4
  4865.3  135.35  4887.5  133.59  4900.3  133.35  4924.4  132.89  4943.4  132.93
    4944  132.74 4944.11   132.7  4944.2  132.68  4944.3  132.64  4981.4  120.85
  4984.8  119.16  4987.5  117.57  4989.3  117.49  5002.6  116.87  5012.9   117.5
  5015.2  119.19  5018.8  120.95  5028.5  123.61  5056.1  131.19 5056.19  131.21
  5056.3  131.24  5056.4  131.27  5060.4  132.37 5065.89  132.54    5066  132.54
 5066.11  132.54  5082.2  133.03  5082.4  133.04  5113.8  132.99    5123  133.01
  5145.2  133.07  5164.7  132.54    5184  132.68  5210.6  132.88  5210.7  132.88
  5225.6   129.1  5228.8  129.16  5240.6   129.4  5243.8  129.66  5255.6   130.6
  5286.2  131.18  5292.5   131.3  5372.5     131  5412.5   129.3  5432.5   130.4
  5447.5   130.5  5452.5   130.4  5457.5   130.1  5472.5   129.7  5487.5   128.8
  5507.5   130.8  5522.5   131.7  5542.5   131.9  5562.5   132.9    5602   133.2
  5602.5   133.2  5615.1     133
BR U #Mann= 5
  4759.9      .2  4772.5     .06  4943.4     .04  5060.4      .1    5602      .2
BR U Banks=4943.4,5060.4
BR D #Sta/Elev= 67
  4759.9  132.35 4760.49  132.37  4760.6  132.37 4760.71  132.37  4761.8   132.4
  4772.5  132.67  4796.3  133.28  4806.7  133.87  4833.3  135.37  4850.8   135.3
  4865.3  135.25  4887.5  133.49  4900.3  133.25  4924.4  132.79  4943.4  132.83
    4944  132.64 4944.11   132.6  4944.2  132.58  4944.3  132.54  4981.4  120.75
  4984.8  119.06  4987.5  117.47  4989.3  117.39  5002.6  116.77  5012.9   117.4
  5015.2  119.09  5018.8  120.85  5028.5  123.51  5056.1  131.09 5056.19  131.11
  5056.3  131.14  5056.4  131.17  5060.4  132.27 5065.89  132.44    5066  132.44
 5066.11  132.44  5082.2  132.93  5082.4  132.94  5113.8  132.89    5123  132.91
  5145.2  132.97  5164.7  132.44    5184  132.58  5210.6  132.78  5210.7  132.78
  5225.6     129  5228.8  129.06  5240.6   129.3  5243.8  129.56  5255.6   130.5
  5286.2  131.08  5292.5   131.2  5372.5   130.9  5412.5   129.2  5432.5   130.3
  5447.5   130.4  5452.5   130.3  5457.5     130  5472.5   129.6  5487.5   128.7
  5507.5   130.7  5522.5   131.6  5542.5   131.8  5562.5   132.8    5602   133.1
  5602.5   133.1  5615.1   132.9
BR D #Mann= 5
  4759.9      .2  4772.5     .06  4943.4     .04  5060.4      .1    5602      .2
BR D Banks=4943.4,5060.4
BC Design=,, 0 ,, 0 ,,,,,,
BC HTab HWMax=135.47

Type RM Length L Ch R = 1 ,4507.6  ,501.5,501.5,501.5
BEGIN DESCRIPTION:
Downstream Section of Bridge/Culvert/Weir
END DESCRIPTION:
XS GIS Cut Line= 2
      2994732.32     13847807.36      2994720.96     13846952.23
#Sta/Elev= 30
  4759.9  132.34  4772.5  132.66  4796.3  133.27  4833.3  135.36  4865.3  135.24
  4887.5  133.48  4943.4  132.82  4981.4  120.74  4987.5  117.46  5002.6  116.76
  5012.9  117.39  5018.8  120.84  5060.4  132.26  5082.4  132.93  5164.7  132.43
  5210.7  132.77  5225.6  128.99  5240.6  129.29  5255.6  130.49  5292.5  131.19
  5372.5  130.89  5412.5  129.19  5432.5  130.29  5447.5  130.39  5487.5  128.69
  5522.5  131.59  5542.5  131.79  5562.5  132.79    5602  133.09  5615.1  132.89
#Mann= 5 , 1 , 0
  4759.9      .2       0  4772.5     .06       0  4943.4     .04       0
  5060.4      .1       0    5602      .2       0
#XS Ineff= 2 , 0
       0    4933     133  5050.3       0   129.6
Permanent Ineff=
       F       F
Bank Sta=4943.4,5060.4
XS Rating Curve= 0
Exp/Cntr=.5,.3

Type RM Length L Ch R = 1 ,4006.1  ,440.1,439.9,439.7
BEGIN DESCRIPTION:
Cross Section 4006.1-Interpolated
END DESCRIPTION:
XS GIS Cut Line= 5
      2995208.01     13847848.56       2995209.8     13847566.27
       2995209.8     13847434.06      2995202.65     13847310.78
      2995009.69     13847007.05
#Sta/Elev= 30
  4731.3   131.1  4804.5   132.1  4834.5   136.2  4849.5     136  4894.5     132
  4924.5   131.3  4939.5   130.1  4969.5   123.7  4984.5     119  4999.5   116.5
  5007.1  117.47  5044.5     128  5059.5   129.9  5104.5     131  5164.5     130
  5179.6   131.1  5209.6   130.5  5221.5  128.44  5224.6   127.9  5239.7   128.1
  5254.7   130.1  5269.3   130.6  5323.1   131.1  5376.4   130.5    5412   128.4
  5447.5   130.1  5485.6   129.5  5550.8   130.2  5605.1   132.2  5629.1   132.2
#Mann= 4 , 1 , 0
  4731.3     .06       0  4939.5     .04       0  5059.5      .1       0
  5221.5      .2       0
Bank Sta=4939.5,5059.5
XS Rating Curve= 0
Exp/Cntr=.3,.1

Type RM Length L Ch R = 1 ,3566.2  ,968.7,969.4,971.4
BEGIN DESCRIPTION:
Cross Section 3566.2
END DESCRIPTION:
XS GIS Cut Line= 2
      2995649.47     13847821.16      2995649.47     13847351.75
#Sta/Elev= 21
  4770.4  129.45  4803.7  129.96  4823.7  135.69  4855.2  135.74    4874  132.63
  4949.3  131.28    4994  116.94  4996.7  116.75  4999.5  116.27  5003.2  116.77
  5007.1  117.24  5053.9  131.32  5146.1  130.59  5160.4   128.9  5170.4   129.4
  5175.4   129.9  5190.4   130.3  5205.4   130.3  5220.4   129.5  5221.5  129.51
  5239.8   129.7
#Mann= 4 , 1 , 0
  4770.4     .06       0  4949.3     .04       0  5053.9      .1       0
  5221.5      .2       0
Bank Sta=4949.3,5053.9
XS Rating Curve= 0
Exp/Cntr=.3,.1

Type RM Length L Ch R = 1 ,2596.8  ,1029.2,1030.5,1034.8
BEGIN DESCRIPTION:
Cross Section 2596.8
END DESCRIPTION:
XS GIS Cut Line= 2
      2996611.93      13847850.6      2996624.35     13847409.52
#Sta/Elev= 17
  4766.6  129.01  4815.4  129.49  4824.5  132.69  4855.2  132.95  4866.6  130.12
  4946.2  130.41  4990.4  116.69  4992.5  116.36  4997.6   115.9  5007.5  116.32
  5008.7  116.63  5052.1  130.14  5143.1  128.73  5154.9   128.3  5184.1  129.23
  5204.9   129.9  5207.8   129.9
#Mann= 4 , 1 , 0
  4766.6     .06       0  4946.2     .04       0  5052.1      .1       0
  5184.1      .2       0
Bank Sta=4946.2,5052.1
XS Rating Curve= 0
Exp/Cntr=.3,.1

Type RM Length L Ch R = 1 ,1566.3  ,811,806.4,799.4
BEGIN DESCRIPTION:
Cross Section 1566.3
END DESCRIPTION:
XS GIS Cut Line= 3
      2997563.13     13848196.64      2997628.12     13847864.46
      2997671.45     13847387.85
#Sta/Elev= 19
  4432.4   128.7  4557.4   127.7  4770.9   127.7  4815.9     128  4830.9   128.9
  4845.9     129  4875.8  127.26  4948.8   128.1  4989.1   116.4  4991.8  116.16
  4999.2  115.86  5008.2   116.2  5013.9  116.75  5057.1  128.23  5151.9  127.47
  5160.9   126.6  5220.9   128.5  5228.3  128.53  5249.5   128.6
#Mann= 4 , 1 , 0
  4432.4     .06       0  4948.8     .04       0  5057.1      .1       0
  5228.3      .2       0
Bank Sta=4948.8,5057.1
XS Rating Curve= 0
Exp/Cntr=.3,.1

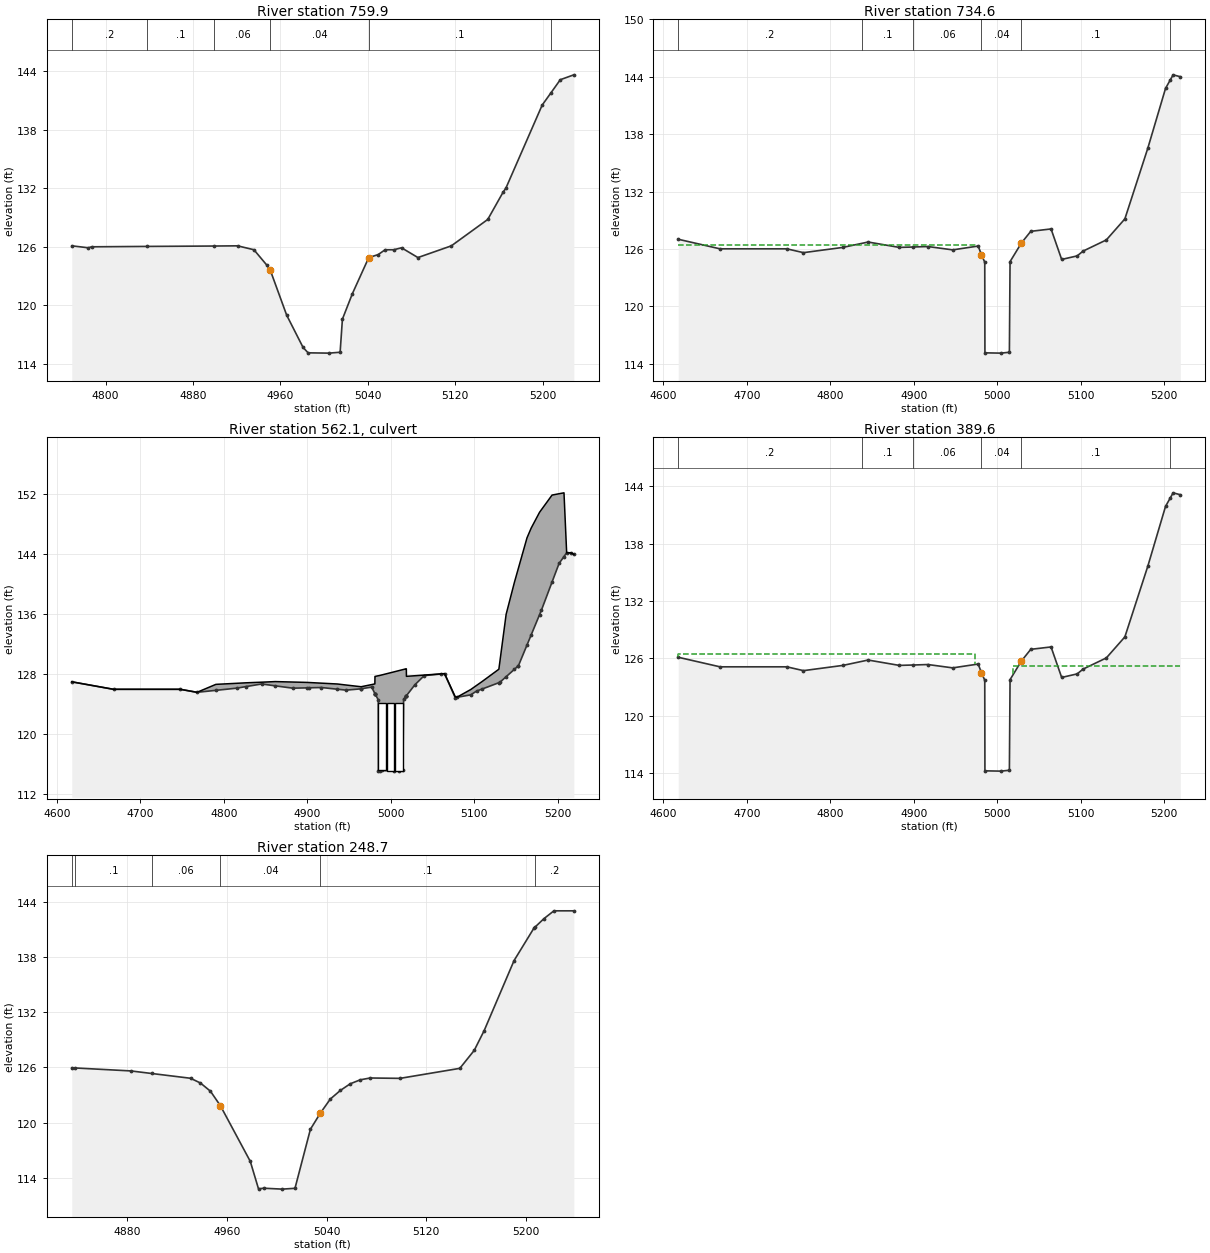
Type RM Length L Ch R = 1 ,759.9   ,17.2,25.3,9.3
BEGIN DESCRIPTION:
Cross Section 759.9-Interpolated
END DESCRIPTION:
XS GIS Cut Line= 5
      2998480.04     13847880.45      2998457.07     13847725.05
      2998454.71      13847634.4        2998450.     13847540.22
      2998399.38     13847434.27
#Sta/Elev= 30
    4769   126.1  4784.2   125.9  4787.1     126  4838.2  126.04  4899.5  126.08
  4920.7   126.1  4935.7   125.7  4947.7   124.1  4950.7   123.6  4965.7     119
  4980.7   115.7  4985.3  115.15  5004.4  115.12  5014.6  115.21  5016.7   118.6
  5025.8   121.2  5040.8   124.9  5049.4   125.2  5055.8   125.7  5063.7   125.7
  5070.8   125.9  5085.8   124.9  5116.4   126.1  5149.7   128.8  5163.8   131.6
  5166.3     132  5199.5   140.5  5207.5  141.75  5216.1   143.1  5228.5   143.6
#Mann= 6 , 1 , 0
    4769      .2       0  4838.2      .1       0  4899.5     .06       0
  4950.7     .04       0  5040.8      .1       0  5207.5      .2       0
Bank Sta=4950.7,5040.8
XS Rating Curve= 0
Exp/Cntr=.5,.3

Type RM Length L Ch R = 1 ,734.6   ,345,345,345
BEGIN DESCRIPTION:
Upstream Section of Bridge/Culvert/Weir
END DESCRIPTION:
XS GIS Cut Line= 2
      2998487.22     13848033.68      2998502.17     13847432.56
#Sta/Elev= 30
    4618  127.01    4668  126.01    4748  126.01    4768  125.61  4815.3  126.16
  4845.4  126.72  4882.7  126.16  4899.5   126.2    4917  126.25  4946.7   125.9
  4977.2   126.3  4981.1  125.41  4985.1  124.61  4985.3  115.13  5004.4   115.1
  5014.6  115.19  5015.4  124.67    5029  126.62  5040.2  127.84  5064.5  128.09
  5077.2   124.9  5095.8  125.27  5102.8  125.77  5130.7  126.94  5152.9  129.14
  5180.4  136.54  5201.6  142.79  5207.5  143.71  5210.7  144.21  5219.3  144.01
#Mann= 6 , 1 , 0
    4618      .2       0  4838.2      .1       0  4899.5     .06       0
  4981.1     .04       0    5029      .1       0  5207.5      .2       0
#XS Ineff= 2 , 0
       0    4974  126.42  5019.2       0   125.2
Permanent Ineff=
       F       F
Bank Sta=4981.1,5029
XS Rating Curve= 0
Exp/Cntr=.5,.3

Type RM Length L Ch R = 2 ,562.1   ,,,
BEGIN DESCRIPTION:
MASON ROAD-FRONTAGE ROAD
Structure ID: T13-2
END DESCRIPTION:
Bridge Culvert--1,0,-1,-1, 0
Deck Dist Width WeirC Skew NumUp NumDn MinLoCord MaxHiCord MaxSubmerge Is_Ogee
10,325,3,0, 59, 59, , , .95, 0, 1,1,,
    4618    4668    4748    4768  4790.6  4815.3  4827.1  4845.4  4861.8  4882.7
  4899.5  4901.7    4917  4936.1  4946.7    4964  4964.4  4977.2 4980.99  4981.1
  4981.2 4981.31  4985.1  4985.3    4987  4989.4  5004.4  5009.7  5014.6  5015.4
  5018.1 5018.59  5018.7 5018.81    5029  5040.2  5060.5  5064.5  5077.2  5079.2
  5095.8  5102.8  5109.1  5129.5  5130.7  5138.2  5148.2  5152.8  5152.9  5163.2
  5168.2  5178.2  5180.4  5193.2  5201.6  5207.5  5210.7  5215.7  5219.3
     127     126     126   125.6  126.66   126.8  126.87  126.95  127.03  126.97
  126.92  126.91  126.82  126.71  126.57  126.35  126.34  126.63  126.72  127.72
  127.72  127.72  127.81  127.81  127.85  127.92  128.34  128.49  128.63  128.65
  128.73  128.73  128.73  127.73  127.81   127.9  128.06  128.09  125.03  124.94
  125.97  126.52  127.01  128.68  129.69     136   140.3  142.11  142.15   146.2
   147.5   149.6  149.94   151.9  152.08   152.2   144.2   144.2     144
     127     126     126   125.6  125.86  126.15  126.37  126.71  126.46  126.15
  126.19   126.2  126.24  126.01  125.89  126.06  126.07  126.29  125.43   125.4
  125.38  125.36   124.6  115.12  115.15  115.19  115.09  115.17  115.18  124.66
  125.05  125.12  125.13  125.15  126.61  127.83  128.04  128.08  124.89  124.93
  125.26  125.76  126.02  126.88  126.93  127.68  128.67  129.13  129.13   131.9
  133.25  135.94  136.53   140.3  142.78   143.7   144.2   144.2     144
    4618    4668    4748    4768  4790.6  4815.3  4827.1  4845.4  4861.8  4882.7
  4899.5  4901.7    4917  4936.1  4946.7    4964  4964.4  4977.2 4980.99  4981.1
  4981.2 4981.31  4985.1  4985.3    4987  4989.4  5004.4  5009.7  5014.6  5015.4
  5018.1 5018.59  5018.7 5018.81    5029  5040.2  5060.5  5064.5  5077.2  5079.2
  5095.8  5102.8  5109.1  5129.5  5130.7  5138.2  5148.2  5152.8  5152.9  5163.2
  5168.2  5178.2  5180.4  5193.2  5201.6  5207.5  5210.7  5215.7  5219.3
     127     126     126   125.6  126.66   126.8  126.87  126.95  127.03  126.97
  126.92  126.91  126.82  126.71  126.57  126.35  126.34  126.63  126.72  127.72
  127.72  127.72  127.81  127.81  127.85  127.92  128.34  128.49  128.63  128.65
  128.73  128.73  128.73  127.73  127.81   127.9  128.06  128.09  125.03  124.94
  125.97  126.52  127.01  128.68  129.69     136   140.3  142.11  142.15   146.2
   147.5   149.6  149.94   151.9  152.08   152.2   144.2   144.2     144
  126.21  125.21  125.21  124.81  125.07  125.36  125.58  125.92  125.67  125.36
   125.4  125.41  125.45  125.22   125.1  125.27  125.28   125.5  124.64  124.61
  124.59  124.57  123.81  114.33  114.36   114.4   114.3  114.38  114.39  123.87
  124.26  124.33  124.34  124.36  125.82  127.04  127.25  127.29   124.1  124.14
  124.47  124.97  125.23  126.09  126.14  126.89  127.88  128.34  128.34  131.11
  132.46  135.15  135.74  139.51  141.99  142.91  143.41  143.41  143.21
BR Coef= 1 , 0 , 0 ,1.25, 0 ,,,.8,-1,2,0,
WSPro=,,,, 1 ,,,, 0 ,,,, 0 ,,,,-1 ,-1 ,-1 , 0 , 0 , 0 , 0 , 0
Culvert=2,9,9,325,.015,.2,1,8,1,115.19,4989.4,114.41,4989.4,Culvert #1  , 0 ,10
Culvert Bottom n=.015
Culvert=2,9,9,325,.015,.2,1,8,1,115.15,4999.7,114.37,4999.7,Culvert #2  , 0 ,10
Culvert Bottom n=.015
Culvert=2,9,9,325,.015,.2,1,8,1,115.17,5009.8,114.4,5009.8,Culvert #3  , 0 ,10
Culvert Bottom n=.015
BR U #Sta/Elev= 59
    4618     127    4668     126    4748     126    4768   125.6  4790.6  125.86
  4815.3  126.15  4827.1  126.37  4845.4  126.71  4861.8  126.46  4882.7  126.15
  4899.5  126.19  4901.7   126.2    4917  126.24  4936.1  126.01  4946.7  125.89
    4964  126.06  4964.4  126.07  4977.2  126.29 4980.99  125.43  4981.1   125.4
  4981.2  125.38 4981.31  125.36  4985.1   124.6  4985.3  115.12    4987  115.15
  4989.4  115.19  5004.4  115.09  5009.7  115.17  5014.6  115.18  5015.4  124.66
  5018.1  125.05 5018.59  125.12  5018.7  125.13 5018.81  125.15    5029  126.61
  5040.2  127.83  5060.5  128.04  5064.5  128.08  5077.2  124.89  5079.2  124.93
  5095.8  125.26  5102.8  125.76  5109.1  126.02  5129.5  126.88  5130.7  126.93
  5138.2  127.68  5148.2  128.67  5152.8  129.13  5152.9  129.13  5163.2   131.9
  5168.2  133.25  5178.2  135.94  5180.4  136.53  5193.2   140.3  5201.6  142.78
  5207.5   143.7  5210.7   144.2  5215.7   144.2  5219.3     144
BR U #Mann= 6
    4618      .2  4838.2      .1  4899.5     .06  4981.1     .04    5029      .1
  5207.5      .2
BR U Banks=4981.1,5029
BR D #Sta/Elev= 59
    4618  126.21    4668  125.21    4748  125.21    4768  124.81  4790.6  125.07
  4815.3  125.36  4827.1  125.58  4845.4  125.92  4861.8  125.67  4882.7  125.36
  4899.5   125.4  4901.7  125.41    4917  125.45  4936.1  125.22  4946.7   125.1
    4964  125.27  4964.4  125.28  4977.2   125.5 4980.99  124.64  4981.1  124.61
  4981.2  124.59 4981.31  124.57  4985.1  123.81  4985.3  114.33    4987  114.36
  4989.4   114.4  5004.4   114.3  5009.7  114.38  5014.6  114.39  5015.4  123.87
  5018.1  124.26 5018.59  124.33  5018.7  124.34 5018.81  124.36    5029  125.82
  5040.2  127.04  5060.5  127.25  5064.5  127.29  5077.2   124.1  5079.2  124.14
  5095.8  124.47  5102.8  124.97  5109.1  125.23  5129.5  126.09  5130.7  126.14
  5138.2  126.89  5148.2  127.88  5152.8  128.34  5152.9  128.34  5163.2  131.11
  5168.2  132.46  5178.2  135.15  5180.4  135.74  5193.2  139.51  5201.6  141.99
  5207.5  142.91  5210.7  143.41  5215.7  143.41  5219.3  143.21
BR D #Mann= 6
    4618      .2  4838.2      .1  4899.5     .06  4981.1     .04    5029      .1
  5207.5      .2
BR D Banks=4981.1,5029
BC Design=,, 0 ,, 0 ,,,,,,
BC HTab HWMax=144.21

Type RM Length L Ch R = 1 ,389.6   ,140.9,140.9,140.9
BEGIN DESCRIPTION:
Downstream Section of Bridge/Culvert/Weir
END DESCRIPTION:
XS GIS Cut Line= 2
      2998832.08     13848043.42      2998847.03     13847442.31
#Sta/Elev= 30
    4618  126.11    4668  125.11    4748  125.11    4768  124.71  4815.3  125.26
  4845.4  125.82  4882.7  125.26  4899.5   125.3    4917  125.35  4946.7     125
  4977.2   125.4  4981.1  124.51  4985.1  123.71  4985.3  114.23  5004.4   114.2
  5014.6  114.29  5015.4  123.77    5029  125.72  5040.2  126.94  5064.5  127.19
  5077.2     124  5095.8  124.37  5102.8  124.87  5130.7  126.04  5152.9  128.24
  5180.4  135.64  5201.6  141.89  5207.5  142.81  5210.7  143.31  5219.3  143.11
#Mann= 6 , 1 , 0
    4618      .2       0  4838.2      .1       0  4899.5     .06       0
  4981.1     .04       0    5029      .1       0  5207.5      .2       0
#XS Ineff= 2 , 0
       0    4974  126.42  5019.2       0   125.2
Permanent Ineff=
       F       F
Bank Sta=4981.1,5029
XS Rating Curve= 0
Exp/Cntr=.5,.3

Type RM Length L Ch R = 1 ,248.7   ,0,0,0
BEGIN DESCRIPTION:
Cross Section 248.7-Interpolated
END DESCRIPTION:
XS GIS Cut Line= 5
      2998918.01     13847820.24      2998945.18     13847781.41
      2998965.78     13847671.04      2998974.61      13847507.7
      2998977.94     13847427.72
#Sta/Elev= 30
  4835.3  125.96  4838.2  125.94  4882.7  125.62  4899.5  125.34  4930.7  124.82
  4938.7   124.3  4946.7  123.41  4954.7  121.83  4978.7  115.77  4985.3  112.78
  4989.4  112.85  5004.4  112.75  5014.6  112.84    5027  119.27    5035  121.03
    5043  122.56    5051  123.49    5059  124.22    5067  124.65    5075  124.85
    5099  124.81    5147   125.9  5158.6  127.86  5166.6  130.02  5190.6  137.64
  5206.6  141.18  5207.5  141.29  5214.6   142.2  5222.6  143.05  5238.6  143.05
#Mann= 6 , 1 , 0
  4835.3      .2       0  4838.2      .1       0  4899.5     .06       0
  4954.7     .04       0    5035      .1       0  5207.5      .2       0
Bank Sta=4954.7,5035
XS Rating Curve= 0
Exp/Cntr=.3,.1

Chan Stop Cuts=-1